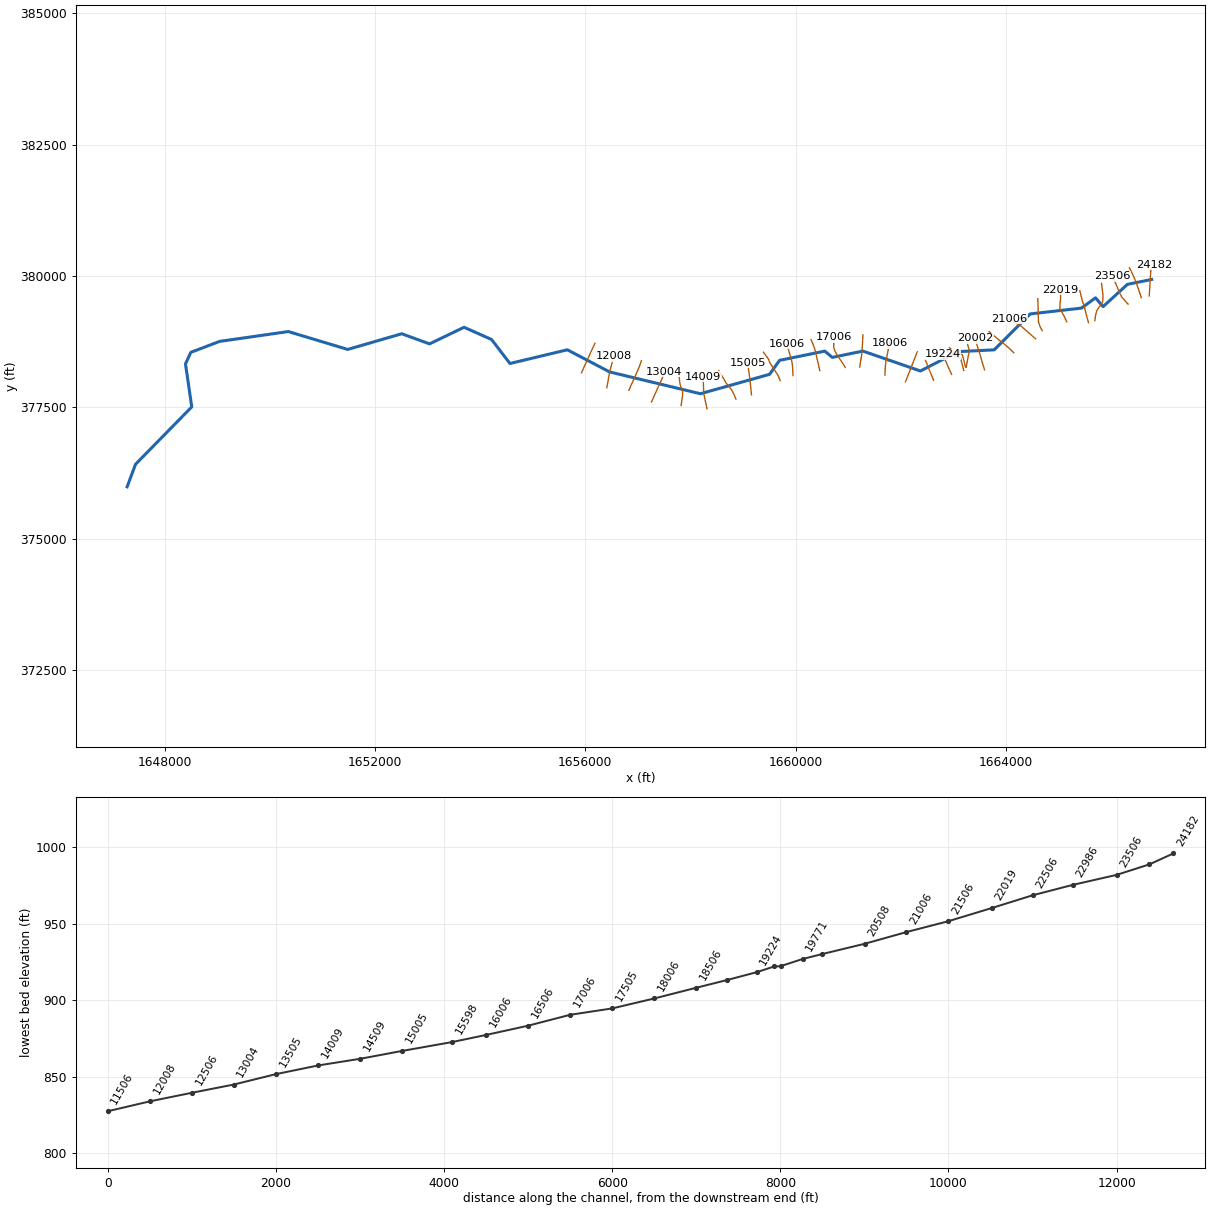
--- RICHWDRN.prj (project) ---

Proj Title=RICHWDRN
Current Plan=p01
Default Exp/Contr=0,0
English Units
Geom File=g01
Flow File=f01
Plan File=p01
BEGIN DESCRIPTION:
---------- MODELED AS PART OF WVEMD CTP PROGRAM, 2023----------
Stream Name: Richwood Run
Flood Zone:  AFH
Wetzel County, WV
HEC-RAS Version: RAS 6.3
Vertical Datum: NAVD88
Projection: NAD 1983 StatePlane West Virginia S FIPS 4702 (US Feet)
Terrain: 1-meter West Virginia FEMA R3 South Central (collected 2018-2020)
Land Use: 2019 NLCD
Hydrologic Method:
WV 2010 Regional Regression Equations
Additional Model Notes:
None
END DESCRIPTION:
DSS Export Rating Curves= 0
DSS Export Rating Curve Sorted= 0
DSS Export Volume Flow Curves= 0
DXF OffsetX= 0
DXF OffsetY= 0
DXF ScaleX= 0
DXF ScaleY= 0

--- RICHWDRN.p01 (plan) ---

Plan Title=Floodplain
Program Version=6.30
Short Identifier=Floodplain
Geom File=g01
Flow File=f01
Subcritical Flow
K Sum by GR= 0
Std Step Tol= 0.01
Critical Tol= 0.01
Num of Std Step Trials= 20
Max Error Tol= 0.3
Flow Tol Ratio= 0.001
Split Flow NTrial= 30
Split Flow Tol= 0.02
Split Flow Ratio= 0.02
Log Output Level= 0
Friction Slope Method= 1
Unsteady Friction Slope Method= 2
Unsteady Bridges Friction Slope Method= 1
Parabolic Critical Depth
Global Vel Dist= 0 , 0 , 0
Global Log Level= 0
CheckData=False
Encroach Param=-1 ,0,0, 0
Mapping Interval=1HOUR
Computation Time Step Use Courant=        0
Computation Time Step Use Time Series=    0
Computation Time Step Count To Double=0
Computation Time Step Max Doubling=0
Computation Time Step Max Halving=0
Computation Time Step Residence Courant=0
Run HTab= 0
Run UNet= 0
Run Sediment= 0
Run PostProcess= 0
Run WQNet= 0
Run RASMapper=-1
UNET Theta= 0
UNET Theta Warmup= 0
UNET ZTol= 0
UNET ZSATol= 0
UNET MxIter= 0
UNET Max Iter WO Improvement= 0
UNET MaxInSteps= 0
UNET DtIC= 0
UNET DtMin= 0
UNET MaxCRTS= 0
UNET WFStab= 0
UNET SFStab= 0
UNET WFX= 1
UNET SFX= 1
UNET Gravity=32.17405
UNET 1D Methodology=Finite Difference
UNET DSS MLevel= 1
UNET Pardiso=0
UNET DZMax Abort= 0
UNET Use Existing IB Tables= 0
UNET Froude Reduction=False
UNET Froude Limit= 0
UNET Froude Power= 0
UNET D1 Cores= 0
UNET WindReference=Eulerian
UNET WindDragFormulation=Hsu (1988)
UNET D2 Coriolis=0
UNET D2 Cores= 0
UNET D2 Theta= 1
UNET D2 Theta Warmup= 1
UNET D2 Z Tol= 0.01
UNET D2 Volume Tol= 0.01
UNET D2 Max Iterations= 20
UNET D2 Equation= 0
UNET D2 RampUpFraction=0.1
UNET D2 TimeSlices= 1
UNET D2 Turbulence Formulation=Non-Conservative (original)
UNET D2 Eddy Viscosity=0.3
UNET D2 Transverse Eddy Viscosity=0.1
UNET D2 Smagorinsky Mixing=0
UNET D2 BCVolumeCheck=0
UNET D2 Cores=0
UNET D2 SolverType=PARDISO (Direct)
UNET D2 Minimum Iterations= 3
UNET D2 Maximum Iterations= 30
UNET D2 Restart Number= 10
UNET D2 Relaxation Coeff=1.3
UNET D2 SOR Precondition Iterations= 10
UNET D2 ILUT Maximum Fill= 8
UNET D2 ILUT Tolerance=1E-08
UNET D2 Convergence Tolerance=0.00001
UNET D1D2 MaxIter= 0
UNET D1D2 ZTol=0.01
UNET D1D2 QTol=0.1
UNET D1D2 MinQTol=1
Write IC File= 0
Write IC File at Fixed DateTime=0
Write IC File at Sim End=0
Echo Input=False
Echo Parameters=False
Echo Output=False
Write Detailed= 0
HDF Write Warmup=0
HDF Write Time Slices=0
HDF Flush=0
HDF Compression= 1
HDF Chunk Size= 1
HDF Spatial Parts= 1
HDF Use Max Rows=0
HDF Fixed Rows= 1
Calibration Method= 0
Calibration Iterations= 20
Calibration Max Change=0.05
Calibration Tolerance=0.2
Calibration Maximum=1.5
Calibration Minimum=0.5
Calibration Optimization Method= 1
WQ AD Non Conservative
WQ ULTIMATE=-1
WQ Max Comp Step=1HOUR
WQ Output Interval=15MIN
WQ Output Selected Increments= 0
WQ Output face flow=0
WQ Output face velocity=0
WQ Output face area=0
WQ Output face dispersion=0
WQ Output cell volume=0
WQ Output cell surface area=0
WQ Output cell continuity=0
WQ Output cumulative cell continuity=0
WQ Output face conc=0
WQ Output face dconc_dx=0
WQ Output face courant=0
WQ Output face peclet=0
WQ Output face adv mass=0
WQ Output face disp mass=0
WQ Output cell mass=0
WQ Output cell source sink temp=0
WQ Output nsm pathways=0
WQ Output nsm derived pathways=0
WQ Create Restart=0
WQ Fixed Restart=0
WQ System Summary=0
WQ Write To DSS=0
Sorting and Armoring Iterations= 10
XS Update Threshold= 0.02
Bed Roughness Predictor= 0
Hydraulics Update Threshold= 0.02
Energy Slope Method= 1
Volume Change Method= 1
Sediment Retention Method= 0
Sediment TS Multiplier= 1
Warm Up Method= 0
XS Weighting Method= 0
Number of US Weighted Cross Sections= 1
Number of DS Weighted Cross Sections= 1
Upstream XS Weight=0
Main XS Weight=1
Downstream XS Weight=0
Number of DS XS's Weighted with US Boundary= 1
Upstream Boundary Weight= 1
Weight of XSs Associated with US Boundary= 0
Number of US XS's Weighted with DS Boundary= 1
Downstream Boundary Weight= 0.5
Weight of XSs Associated with DS Boundary= 0.5
Percentile Method= 0
Sediment Output Level= 3
Mass or Volume Output= 0
Output Increment Type= 1
Profile and TS Output Increment= 1
Transport Output Increment 1
XS Output Flag= 0
XS Output Increment= 10
Read HDF5 Sediment Hotstart= 0
Sediment Hotstart Type= 0
Write Gradation File= 0
Read Gradation Hotstart= 0
Write HDF5 File= 1
Write Binary Output= 1
Write DSS Sediment File= 0
DSS Sediment Output Type= 1
SV Curve= 0
Specific Gage Flag= 0
Subcell Erosion Methods= 0
Subcell Deposition Methods= 0
Advection Scheme= 1
Matrix Solver= 0
Implicit Weighting Factor= 1
Maximum Outer Loop Convergence Iterations= 5
Convergence Maximum Absolute= 0.001
Convergence RMSE= 0.0001
Grain Fractions Max Abs Error= 0.001
Max Subgrid Regions= 1
Max Subgrid Length Scale= 3.402823E+38
Initial Layer Thickness= 3.402823E+38
Min Layer Thickness= 3.402823E+38
Max Layer Thickness= 3.402823E+38
Number of Layers= 5

--- RICHWDRN.f01 (steady flow) ---

Flow Title=Flow
Program Version=6.31
Number of Profiles= 1
Profile Names=F01pct
River Rch & RM=RICHWDRN,Main,24182
     620
River Rch & RM=RICHWDRN,Main,22506
     690
River Rch & RM=RICHWDRN,Main,21006
     768
River Rch & RM=RICHWDRN,Main,19771
     942
River Rch & RM=RICHWDRN,Main,18506
    1050
River Rch & RM=RICHWDRN,Main,15598
    1180
River Rch & RM=RICHWDRN,Main,11506
    1840
River Rch & RM=RICHWDRN,Main,6998
    2050
Boundary for River Rch & Prof#=RICHWDRN,Main            , 1
Up Type= 0
Dn Type= 3
Dn Slope=0.00796
DSS Import GetInterval= 0
DSS Import GetPeak= 0
DSS Import FillOption= 0

--- RICHWDRN.g01 (geometry) ---

Geom Title=Geometry
Program Version=6.30

River Reach=RICHWDRN        ,Main
Reach XY= 30
     1666777.088      379932.418     1666316.425      379840.164
     1665852.738      379415.798      1665708.46      379583.064
     1665440.773      379387.064     1664463.794      379276.057
     1663781.118      378592.474     1663091.789      378558.295
     1662376.749      378190.188     1661281.504      378568.881
     1660698.946      378449.103      1660556.18      378568.579
     1659694.744      378392.239     1659506.608       378126.67
     1658189.349      377757.051     1656460.731      378172.343
      1655657.37      378593.684     1654565.067      378332.704
     1654215.761      378789.383     1653691.974      379022.369
     1653035.347      378706.101     1652505.365      378898.821
     1651477.751      378600.448     1650348.959      378940.463
     1649039.835      378753.248     1648492.646      378545.041
     1648390.779      378324.789     1648510.541      377506.415
1647440.59357381376414.4471639191647280.58400089375984.678001232

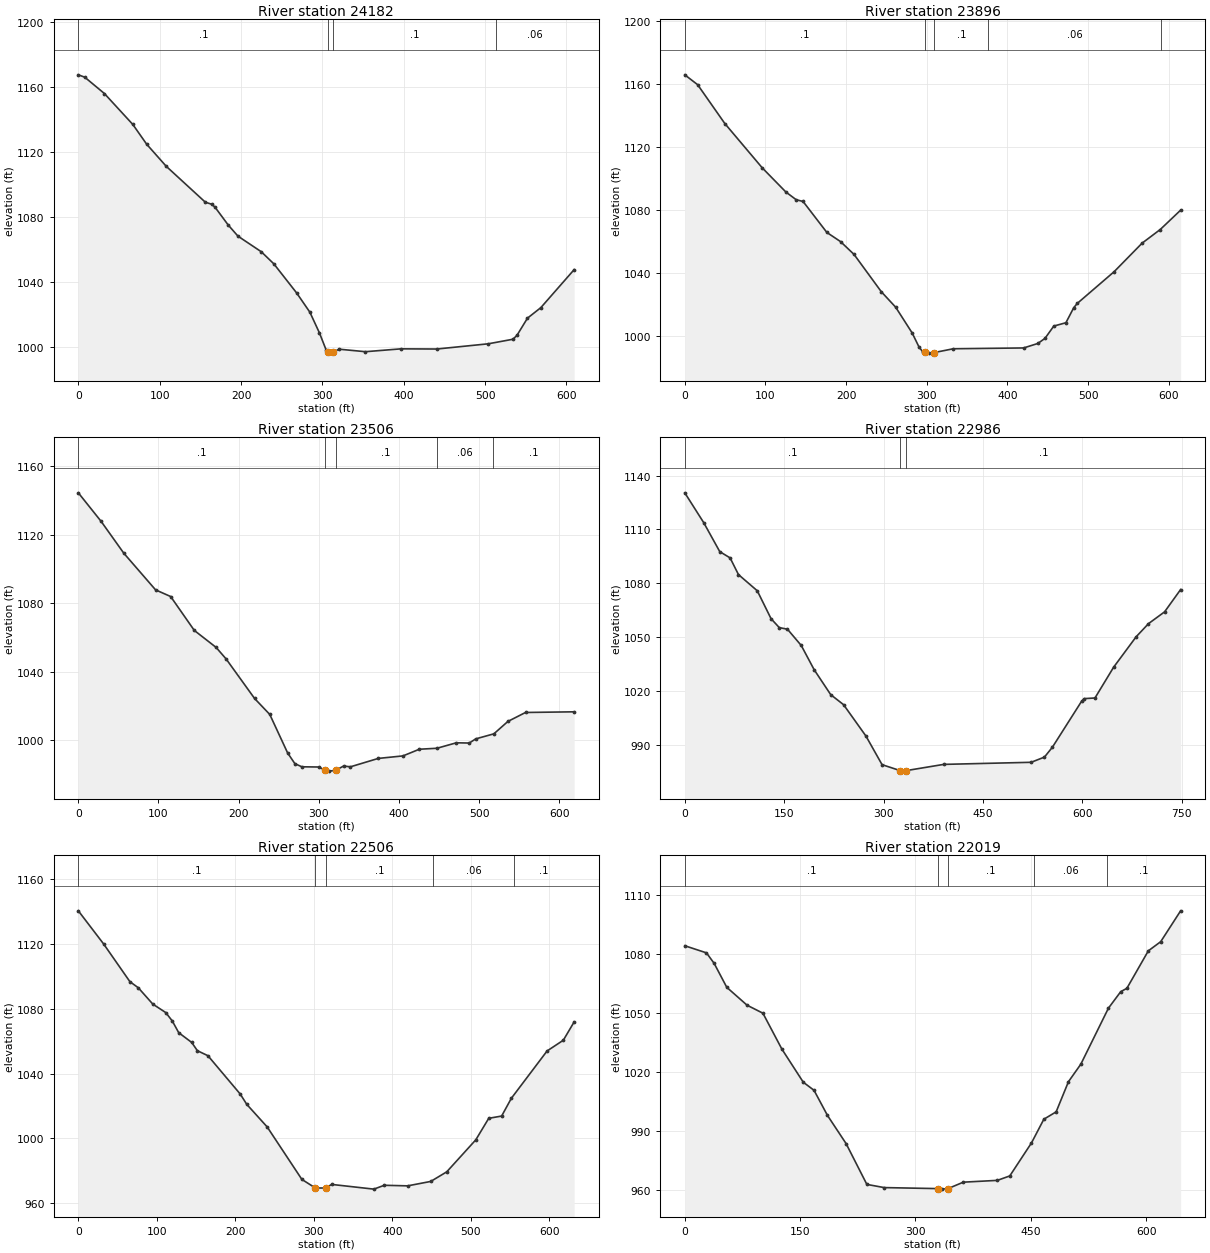
Type RM Length L Ch R = 1 ,24182   ,284.4,285.9,287.3
XS GIS Cut Line= 3
1666730.97666868379620.6205973241666761.71837327380123.547719005
1666822.51435302380210.032140899
#Sta/Elev= 30
       0 1167.62     7.9 1166.16      32 1156.11      67 1137.03    84.1 1124.81
   108.1 1111.24   156.2  1089.1   164.2 1087.84   168.2 1085.96   184.3 1075.05
   196.3 1068.19   224.9 1058.61   240.4 1051.13   268.4 1033.21   284.7 1021.32
   296.5 1008.51   304.5  998.28   307.4996.6975   308.5  996.12   313.2996.6827
   320.5  998.55     353     997   396.7  998.76   440.7  998.65   503.9 1001.86
   534.4 1004.68   539.3 1007.09   552.2 1017.67   568.6 1024.14   609.6 1047.59
#Mann= 4 ,-1,0
       0      .1       0   307.4    .045       0   313.2      .1       0
  513.87     .06       0
Bank Sta=307.4,313.2
XS Rating Curve= 0 ,0
Exp/Cntr(USF)=0,0
Exp/Cntr=0.3,0.1

Type RM Length L Ch R = 1 ,23896   ,389.8,390.6,389.1
XS GIS Cut Line= 6
1666579.74669079379585.4588285351666498.71207596379828.558736038
1666463.73642413379922.3092047091666433.18169522379991.181442287
1666394.51412163 380070.525115621666352.16709347380155.185379367
#Sta/Elev= 30
       0 1165.72    15.9 1159.46    49.6  1134.8      96 1106.63   125.3 1091.29
   138.1 1086.38   146.6 1085.29   176.1 1065.61     193 1059.82   209.8 1051.65
   243.6 1027.95   261.4 1018.12   281.8  1001.8   290.4  992.77   294.7  989.99
   298.3989.3645   303.2  988.96   309.5  989.35   332.9  991.74     420  992.25
   437.6  995.09   446.5  998.35   457.4 1006.15   472.4 1008.26   482.1  1017.8
   486.6 1020.59   532.2 1040.69   566.9 1058.83   589.3 1067.46   614.6 1079.77
#Mann= 5 ,-1,0
       0      .1       0   298.3    .045       0   309.5      .1       0
  376.31     .06       0  589.92      .1       0
Bank Sta=298.3,309.5
XS Rating Curve= 0 ,0
Exp/Cntr(USF)=0,0
Exp/Cntr=0.3,0.1

Type RM Length L Ch R = 1 ,23506   ,521.3,519.9,511.6
XS GIS Cut Line= 6
    1666329.1928379461.4861258421666263.45539868379533.252714589
1666206.42401667379602.6974575821666171.59140918379669.304935917
1666103.42455076379830.4837474231666028.91256067379995.782301337
#Sta/Elev= 30
       0 1144.54    28.4  1127.9    56.7 1109.31    96.4 1087.88   115.2    1084
   144.7 1064.21   171.9  1054.3   184.4 1047.56   219.9 1024.49   238.9 1015.14
   261.2  992.64   270.2  986.43   278.9  984.59   300.5  984.46   307.7982.4975
   312.8  982.06   320.9982.4814   330.9  985.01   339.6  984.59   374.3  989.48
   405.1  990.95   425.5  994.84   447.5  995.41   471.7   998.6   487.8  998.46
   495.9 1000.89   518.5 1003.83     536 1011.07     558  1016.3   618.7 1016.69
#Mann= 5 ,-1,0
       0      .1       0   307.7    .045       0   320.9      .1       0
  447.35     .06       0  517.35      .1       0
Bank Sta=307.7,320.9
XS Rating Curve= 0 ,0
Exp/Cntr(USF)=0,0
Exp/Cntr=0.3,0.1

Type RM Length L Ch R = 1 ,22986   ,476.2,480.1,482.9
XS GIS Cut Line= 6
1665696.04314767379148.1609650851665709.00079893379249.963911086
1665734.00796676  379342.43780751665843.11896901379500.999826342
1665851.76560526379617.0340430891665823.61572717379856.483367339
#Sta/Elev= 30
       0 1130.38    28.6 1113.76    52.8 1097.66    68.4 1094.18      81  1084.9
   109.4 1075.89   130.2 1060.37   142.6  1055.4     155  1054.5   175.8 1045.45
   195.3 1031.96   220.3 1018.09   239.7 1012.51   273.5  995.04   297.8  979.14
     325975.8578   329.5  975.55   334.5 975.856   390.9   979.3   522.8  980.46
   542.9  983.35   554.9  988.84   599.1 1014.47   603.1 1015.89   619.2 1016.24
   647.4 1033.39   681.3 1050.27     700  1057.6   724.3 1064.17   748.5 1076.58
#Mann= 3 ,-1,0
       0      .1       0     325    .045       0   334.5      .1       0
Bank Sta=325,334.5
XS Rating Curve= 0 ,0
Exp/Cntr(USF)=0,0
Exp/Cntr=0.3,0.1

Type RM Length L Ch R = 1 ,22506   ,487.1,486.9,482.6
XS GIS Cut Line= 6
1665575.77337509379109.444835171 1665549.3994121379199.471558005
1665484.73025009 379453.881154181665456.17650142379524.036197588
1665435.73658167379615.1721701771665408.74582201379717.886531666
#Sta/Elev= 30
       0  1140.4    32.4 1119.85    65.7  1096.7    76.4 1092.93    94.9 1082.85
   111.4 1077.62   119.7 1072.44   127.9 1065.22   144.4 1059.22   151.7  1054.1
   165.1 1051.02   206.3 1027.34   214.6    1021   240.6 1007.07   284.8   974.7
     302969.4033     315969.3839   322.8   971.6   376.5   968.7   389.8  971.07
   419.6  970.72     449  973.45   469.4  979.38   506.4  999.13   522.9  1012.4
   539.3 1013.78   551.7 1024.76   597.2 1053.94   617.9 1060.57   631.7 1071.88
#Mann= 5 ,-1,0
       0      .1       0     302    .045       0     315      .1       0
  452.05     .06       0  555.45      .1       0
Bank Sta=302,315
XS Rating Curve= 0 ,0
Exp/Cntr(USF)=0,0
Exp/Cntr=0.3,0.1

Type RM Length L Ch R = 1 ,22019   ,512.3,513.1,510.8
XS GIS Cut Line= 6
1665161.01731484379126.8834485861665118.11516967379220.887853757
1665029.46180367 379378.252368421665033.13764934379478.879463762
1665042.90075317 379553.768421591665043.48506959379738.455716252
#Sta/Elev= 30
       0 1084.05    28.2 1080.43    38.2 1075.08    54.6 1062.92      81 1053.83
   101.6 1049.77   126.2 1031.57   154.1 1014.69   168.1 1010.57   185.6  997.79
   209.8  983.49   236.8  962.75   259.4  961.13   329.3  960.61   334.3  960.35
   342.3  960.61   362.3  963.89   406.5   964.8   422.7  967.06   450.9  983.83
     467  995.88     483  999.63     499 1014.95   515.1 1023.85     551 1052.32
     567 1060.71     575 1062.42   602.9 1081.47     619 1086.12   644.9  1101.8
#Mann= 5 ,-1,0
       0      .1       0   329.3    .045       0   342.3      .1       0
   454.7     .06       0  549.38      .1       0
Bank Sta=329.3,342.3
XS Rating Curve= 0 ,0
Exp/Cntr(USF)=0,0
Exp/Cntr=0.3,0.1

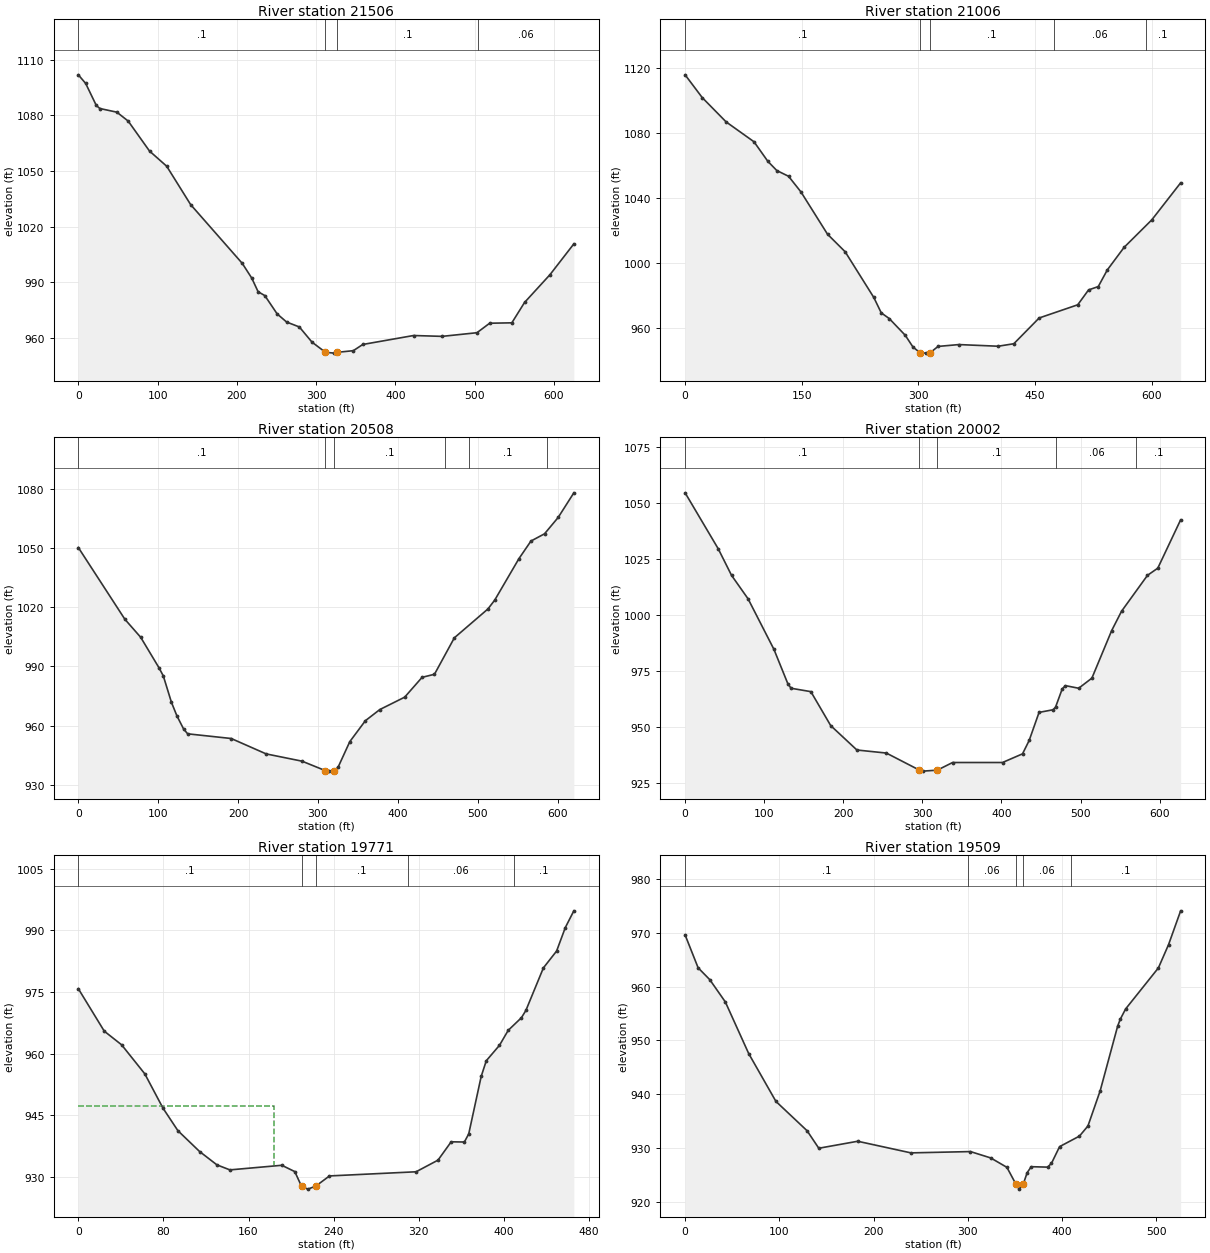
Type RM Length L Ch R = 1 ,21506   ,492.2,499.6,503.4
XS GIS Cut Line= 6
1664692.98216167378956.2253253461664647.20764692379047.873436004
1664621.44982442379135.4185364991664616.01742059379385.359637678
1664613.93277909379472.8233735111664609.75398168379566.656847253
#Sta/Elev= 30
       0 1101.75     9.3 1097.11    22.7 1085.23    27.2  1083.6    48.6 1081.63
    62.9 1076.84    89.8 1060.69   111.5  1052.5   141.7 1031.82   206.8 1000.17
   218.8  992.22   226.8  984.88   235.3  982.79   250.8  972.95   262.8  968.54
   278.8  965.91   294.8  957.72   311.8952.2426   322.8   951.8   326.8  952.24
   346.9  953.12   358.9  956.47   422.9  961.29   458.9  960.83   502.9   962.8
   518.9  967.91   546.9  968.13   562.9  979.09     595  994.07   625.1 1010.67
#Mann= 4 ,-1,0
       0      .1       0   311.8    .045       0   326.8      .1       0
   503.7     .06       0
Bank Sta=311.8,326.8
XS Rating Curve= 0 ,0
Exp/Cntr(USF)=0,0
Exp/Cntr=0.3,0.1

Type RM Length L Ch R = 1 ,21006   ,497.5,498.4,497.9
XS GIS Cut Line= 6
1664567.97617809378802.0068017541664375.56022434378971.241043344
1664300.93767017379037.8140729221664233.84036343379078.285776749
 1664149.6561486379127.1954558341664060.77476467379183.379070506
#Sta/Elev= 30
       0 1116.07      22 1102.05    52.7 1087.09    88.6 1074.83   106.4 1062.78
   117.9 1057.12     133 1053.59     149 1043.91   183.1  1017.9   205.8 1007.08
   242.6  978.95   252.2  969.45   262.4  965.99     283  955.68     293   948.4
   302.1  944.93   309.1  944.67   315.1  944.93   325.2   948.8     352  949.94
   402.5  948.92   422.6  950.45   455.2  966.32   504.8  974.44   518.7  983.59
   531.2  985.67   542.8  995.89   564.4 1009.81     600 1026.74   637.1 1049.54
#Mann= 5 ,-1,0
       0      .1       0   302.1    .045       0   315.1      .1       0
  474.61     .06       0  591.97      .1       0
Bank Sta=302.1,315.1
XS Rating Curve= 0 ,0
Exp/Cntr(USF)=0,0
Exp/Cntr=0.3,0.1

Type RM Length L Ch R = 1 ,20508   ,507.6,505.1,498.5
XS GIS Cut Line= 6
1664151.89466117378537.8354140821664082.64315926378605.710278332
1664015.68364751 378666.428660841663956.03547284 378714.71793434
1663876.88963376378775.971092671 1663680.6767716378940.787692174
#Sta/Elev= 30
       0 1050.21    58.3 1013.88    78.1 1004.75   100.8  989.45   106.4  985.21
   116.6  971.82   123.4  965.01   131.9  958.25   136.9  955.88   191.4  953.51
   235.2  945.71   280.1  942.03   308.9937.3057   313.8  936.99   320.6   937.3
   325.2  938.94   339.9  951.92   359.4  962.52   377.5  968.17   408.6  974.44
   430.4  984.48   445.9  986.03   470.8 1004.49   512.8 1019.09   521.3 1023.55
   551.6 1044.54   566.7 1053.48   583.7 1057.15   600.8 1065.44   620.4  1077.9
#Mann= 6 ,-1,0
       0      .1       0   308.9    .045       0   320.6      .1       0
  459.18     .06       0  489.18      .1       0  586.68     .05       0
Bank Sta=308.9,320.6
XS Rating Curve= 0 ,0
Exp/Cntr(USF)=0,0
Exp/Cntr=0.3,0.1

Type RM Length L Ch R = 1 ,20002   ,233.7,231.8,225.6
XS GIS Cut Line= 6
1663596.40200576378212.4735320061663543.39620626378385.822922841
1663524.43430193378458.3890506771663493.18206784378557.323564082
  1663468.356002378632.8552371711663416.23143435378812.396544755
#Sta/Elev= 30
       0 1054.54    41.9 1029.54    58.7 1017.69    79.6 1007.21   112.3  984.65
   129.8  969.37   133.9  967.28     159  965.76   184.1  950.59   217.2   939.7
   254.4  938.34   296.3  930.71   300.5  930.27   318.8   930.7   338.2  934.12
   401.3  934.12   426.6  937.99     435  943.97   447.5   956.5   465.2  957.67
   468.4   958.9   476.8  967.01   480.9  968.44   497.6  967.28   514.3   971.8
   539.3  993.03   551.8 1001.67   584.6 1017.71   597.6 1020.89   626.5 1042.48
#Mann= 5 ,-1,0
       0      .1       0   296.3    .045       0   318.8      .1       0
  469.54     .06       0  570.44      .1       0
Bank Sta=296.3,318.8
XS Rating Curve= 0 ,0
Exp/Cntr(USF)=0,0
Exp/Cntr=0.3,0.1

Type RM Length L Ch R = 1 ,19771   ,260.2,261.9,268.4
XS GIS Cut Line= 3
 1663247.1665602378260.5090664761663306.15483476378574.478914937
  1663270.000731378716.241058636
#Sta/Elev= 30
       0  975.81    24.4  965.48    40.7  962.16    62.5   955.1    79.6  946.75
    93.6  941.28     114  936.21   130.3  932.96   142.5  931.74   191.3  932.86
   203.5  931.32   209.8  927.76   215.7  927.06   223.1927.7684   236.1  930.27
   317.5  931.28   338.1  934.11   350.5  938.57   362.9  938.52     367   940.5
   378.7  954.47   383.5  958.29   395.9  962.04   404.1  965.68   416.5  968.74
   420.7  970.51   437.2  980.88   449.6  984.97   457.8  990.69   465.8  994.75
#Mann= 5 ,-1,0
       0      .1       0   209.8    .045       0   223.1      .1       0
     310     .06       0  409.46      .1       0
#XS Ineff= 2 , 0
             184  947.34
Permanent Ineff=
       F       F
Bank Sta=209.8,223.1
XS Rating Curve= 0 ,0
Exp/Cntr(USF)=0,0
Exp/Cntr=0.3,0.1

Type RM Length L Ch R = 1 ,19509   ,75.1,76.3,78.5
XS GIS Cut Line= 4
1663234.79805102378267.1690329581663174.85835268378499.316436063
1662998.84495279378568.7703722381662926.53674526378633.467189496
#Sta/Elev= 30
       0  969.62    13.8  963.51    26.2   961.3    42.7  957.16    67.5  947.56
    96.4  938.67   129.5  933.21   141.9  929.96   183.2  931.26   239.7   929.1
   302.9  929.34   324.4  928.16   341.6  926.41   351.2 923.265   354.5  922.36
   358.8  923.23   363.1  925.42   367.4  926.53   384.8  926.45   388.9  927.16
   397.5  930.26   418.6  932.22   427.6   934.1   440.6  940.65   459.1  952.64
   461.9  953.94   467.6  955.86   502.4  963.49   513.2  967.83     526   974.1
#Mann= 5 ,-1,0
       0      .1       0  299.76     .06       0   351.2    .045       0
   358.8     .06       0  409.76      .1       0
Bank Sta=351.2,358.8
XS Rating Curve= 0 ,0
Exp/Cntr(USF)=0,0
Exp/Cntr=0.3,0.1

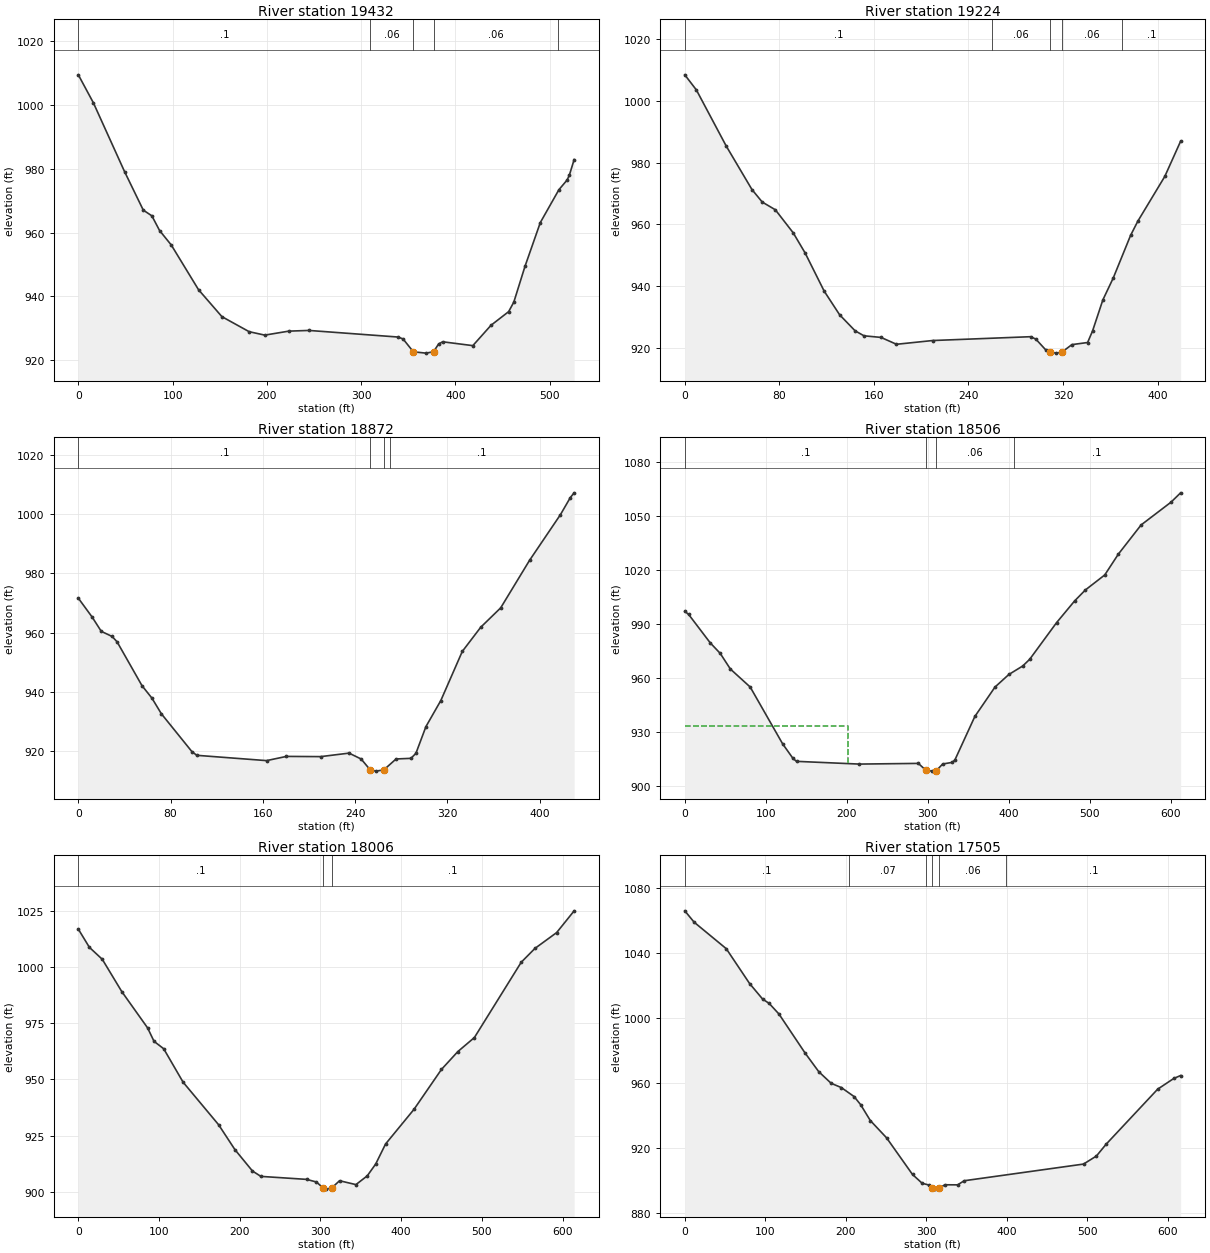
Type RM Length L Ch R = 1 ,19432   ,214.5,208.2,196.3
XS GIS Cut Line= 4
1663200.54679483378201.0450800251663140.60709648378433.192483129
1662964.59369659378502.6464193041662892.28548907378567.343236563
#Sta/Elev= 30
       0  1009.5      16  1000.7      49  979.15    68.9  967.04      78  965.25
    86.2  960.63    98.6  956.09   127.5  942.07   152.3  933.61   181.2  928.89
   197.8  927.81   223.2  929.06   244.6  929.28   339.2  927.21   344.5  926.61
   355.4  922.58   368.7  922.16   376.8  922.58   382.2  925.03   386.5  925.72
   418.5  924.51   437.8   930.9   456.5  935.18     462  938.18   473.8  949.36
   490.1  963.14   509.8  973.44   518.5  976.48   520.9  978.01     526  982.91
#Mann= 5 ,-1,0
       0      .1       0  309.76     .06       0   355.4    .045       0
   376.8     .06       0  508.98      .1       0
Bank Sta=355.4,376.8
XS Rating Curve= 0 ,0
Exp/Cntr(USF)=0,0
Exp/Cntr=0.3,0.1

Type RM Length L Ch R = 1 ,19224   ,352.9,352.7,352.4
XS GIS Cut Line= 2
 1662968.9231751378124.4986790541662800.70924604 378508.78049974
#Sta/Elev= 30
       0 1008.38     9.8 1003.49      35  985.39    56.8  971.31    65.5  967.26
    76.6  964.76    91.7  957.32   101.8   950.8   117.9  938.48     131  930.81
   144.1  925.63   151.6  924.02     166   923.5   179.1  921.28   209.6  922.49
   292.6  923.73     297  922.95   305.7  919.33   309.1  918.76   314.4  918.42
   319.1918.7572   327.5  921.17   340.8  921.85     345   925.6   353.7  935.62
   362.5  942.71   377.2  956.51   383.3  961.08   406.1  975.53   419.5  986.92
#Mann= 5 ,-1,0
       0      .1       0     260     .06       0   309.1    .045       0
   319.1     .06       0     370      .1       0
Bank Sta=309.1,319.1
XS Rating Curve= 0 ,0
Exp/Cntr(USF)=0,0
Exp/Cntr=0.3,0.1

Type RM Length L Ch R = 1 ,18872   ,369.5,366,360.1
XS GIS Cut Line= 2
1662626.86885108378013.4049798741662464.77442876378411.593452109
#Sta/Elev= 30
       0  971.59      12  965.21    19.9  960.41    29.3  958.69    33.6  956.88
    55.2   942.1    63.8  937.91      72  932.63    98.4  919.91   102.7  918.63
   163.2  916.84   180.4  918.26   210.2  918.19   234.7  919.37   245.2  917.39
   253.1  913.71   258.2   913.3   264.9 913.738   275.5   917.4   288.4  917.61
   292.7   919.3   301.4  928.32   314.3   937.1   332.9  953.64   348.9   961.8
   366.2  968.33   391.2  984.33     418  999.74   426.6 1005.52   429.9  1007.1
#Mann= 4 ,-1,0
       0      .1       0   253.1    .045       0   264.9     .06       0
     270      .1       0
Bank Sta=253.1,264.9
XS Rating Curve= 0 ,0
Exp/Cntr(USF)=0,0
Exp/Cntr=0.3,0.1

Type RM Length L Ch R = 1 ,18506   ,498.8,500,501
XS GIS Cut Line= 6
1662091.79182601 377984.11211209  1662185.712898378222.529942334
1662222.36505568378315.5707667621662249.85450201378385.351467088
1662281.92497592378466.7623935041662316.51873876378553.896733671
#Sta/Elev= 30
       0  997.15     4.8  995.36    31.4   979.6    43.8   973.7    56.3  965.03
    80.8  955.01   120.9  923.38   133.7  915.27     138  913.68   215.4  912.16
   288.5  912.54   298.1  908.61   305.9  908.24   310.8908.5638   318.6  912.21
   330.6  913.12   333.7   914.5   358.3  938.64   383.2     955   400.3  961.99
   417.5  966.73   426.1  970.47   459.2  990.79   481.7 1002.98   494.9 1009.02
   518.8 1017.36   535.5 1028.89   563.7 1045.17   600.6 1057.82   612.5 1063.03
#Mann= 4 ,-1,0
       0      .1       0   298.1    .045       0   310.8     .06       0
  406.25      .1       0
#XS Ineff= 2 , 0
          201.98  933.09
Permanent Ineff=
       F       F
Bank Sta=298.1,310.8
XS Rating Curve= 0 ,0
Exp/Cntr(USF)=0,0
Exp/Cntr=0.3,0.1

Type RM Length L Ch R = 1 ,18006   ,501,500.9,501.7
XS GIS Cut Line= 6
 1661701.5701655378110.8300345091661705.39168018378205.455829501
1661710.73550151378293.5025694221661719.21514334378368.255044594
1661738.49036726378466.3798483461661787.88003226378717.825211585
#Sta/Elev= 30
       0 1016.73    13.7 1008.65    29.7 1003.33    53.8  989.01    85.8  972.88
    93.8  966.89   105.8  963.59   129.8  948.75   173.9   929.8   194.1  918.75
   215.8  909.27   226.2  906.89   282.9  905.56   295.1  904.39     303  901.84
   307.3  901.23   314.2901.8322   323.7  904.96     344  903.24     358  907.12
   368.5   912.4   380.7  921.28   415.9  936.66     450  954.43   470.3  962.35
   490.8  968.58   548.8 1002.02   565.8 1008.17   592.7  1015.2   614.4 1024.87
#Mann= 3 ,-1,0
       0      .1       0     303    .045       0   314.2      .1       0
Bank Sta=303,314.2
XS Rating Curve= 0 ,0
Exp/Cntr(USF)=0,0
Exp/Cntr=0.3,0.1

Type RM Length L Ch R = 1 ,17505   ,491.3,499.1,501.6
XS GIS Cut Line= 6
1661220.57834534378265.0590567591661235.80206817378359.211099416
1661250.14784001 378446.683365421661261.53659676378521.315105915
1661268.74130675378621.0727804151661282.38596451378876.959407762
#Sta/Elev= 30
       0 1065.68    11.6 1058.69    51.5 1042.42    80.5    1021    96.7 1011.44
   104.8 1008.81     117 1002.25   149.4  978.32   166.4  966.85   181.8  959.72
   194.4  957.11   210.2  951.61   218.3  946.67   230.4  936.86   250.6  926.24
   282.8  903.73   294.8  898.31   302.8  897.29   306.8895.3075   310.9  894.72
   316.2895.3187   322.9  897.39   338.9  897.35     347  899.87   495.2  910.11
   511.2  915.05   523.2  922.27   587.3  956.13   607.3   962.7   615.8  964.51
#Mann= 6 ,-1,0
       0      .1       0  204.02     .07       0  299.51     .06       0
   306.8    .045       0   316.2     .06       0  399.53      .1       0
Bank Sta=306.8,316.2
XS Rating Curve= 0 ,0
Exp/Cntr(USF)=0,0
Exp/Cntr=0.3,0.1

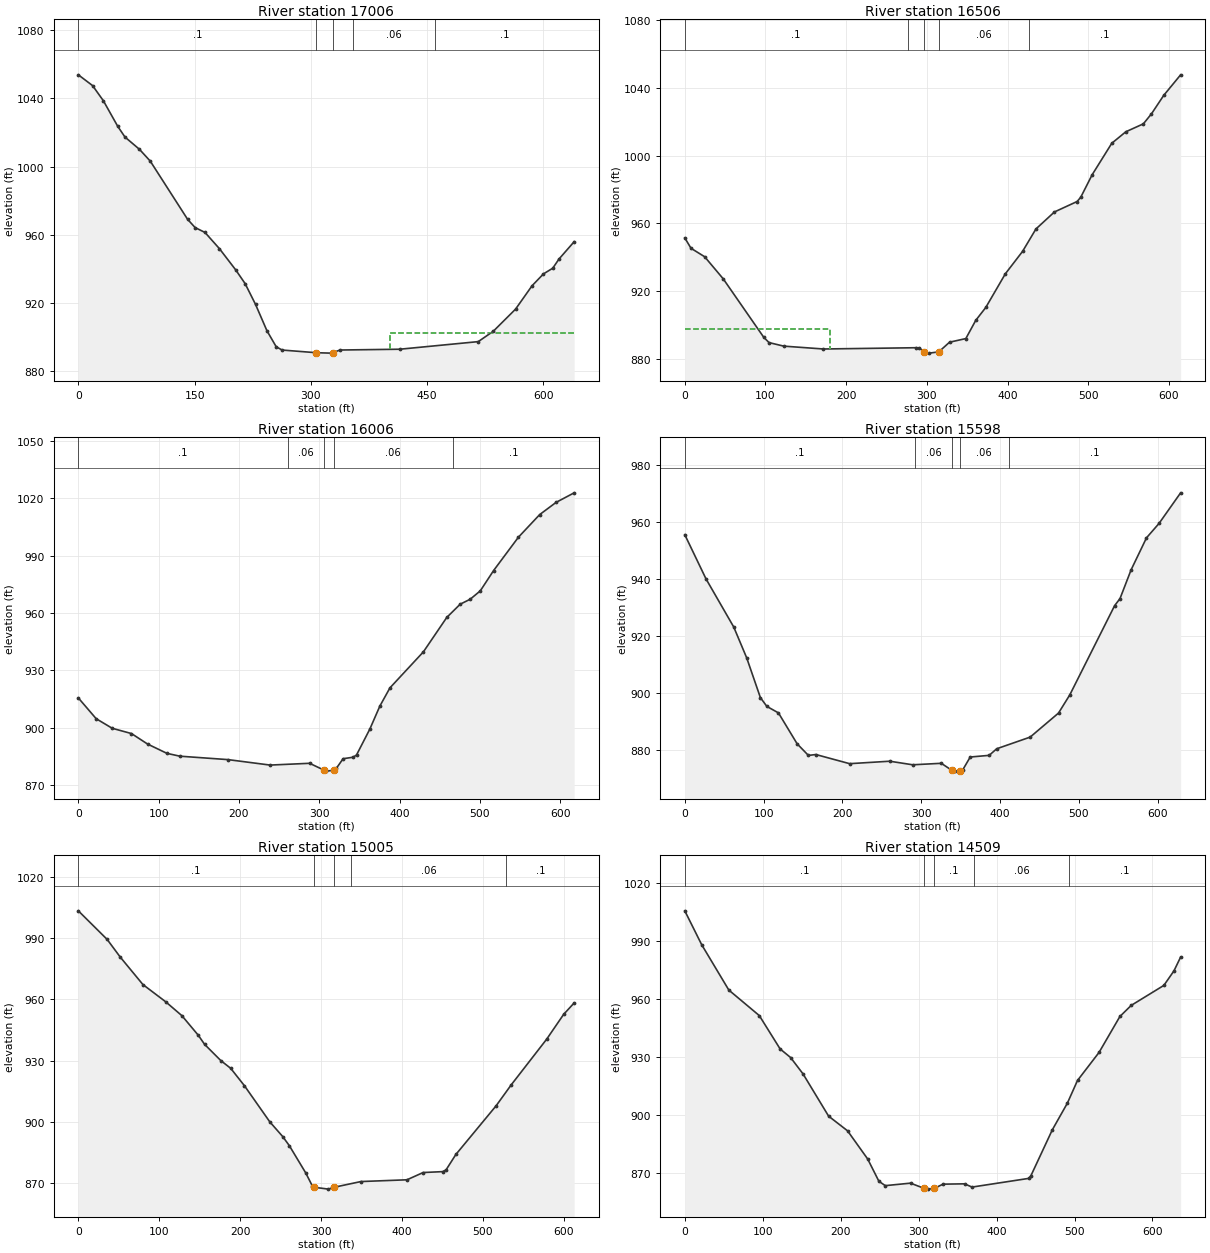
Type RM Length L Ch R = 1 ,17006   ,501.7,500,498.2
XS GIS Cut Line= 6
1660945.60743859378256.7847950911660894.39822343378342.792169005
1660795.23044276378485.470689416 1660747.6688581378573.890460089
 1660726.3519716378646.3689896761660728.03766376378836.102206007
#Sta/Elev= 30
       0  1053.8    18.4 1047.47    32.3 1038.59    50.9 1023.54    60.2 1017.29
    78.9 1010.09    92.8 1003.19     141  969.03   150.7   964.2   163.4  961.35
   182.1   951.8   203.1  939.35   215.2  931.33   228.6  919.17   243.3  903.72
   255.3  894.29   262.9  892.37   306.9 890.805   325.7  890.56   328.3890.7977
   337.5  892.38   414.7  892.85     516  897.31   535.4   903.4   564.1  916.37
   585.4  930.09   600.1  937.04   612.1  940.38   620.1  945.74   639.7  955.92
#Mann= 5 ,-1,0
       0      .1       0   306.9    .045       0   328.3      .1       0
  353.86     .06       0  459.81      .1       0
#XS Ineff= 2 , 0
                          402.42           902.5
Permanent Ineff=
       F       F
Bank Sta=306.9,328.3
XS Rating Curve= 0 ,0
Exp/Cntr(USF)=0,0
Exp/Cntr=0.3,0.1

Type RM Length L Ch R = 1 ,16506   ,499.1,500,499.3
XS GIS Cut Line= 6
1660461.53918101378197.0135891741660440.85090217378288.452710763
1660382.13087526378544.3002961731660362.86877467 378616.82967867
1660332.31667042 378699.592964591660295.23898867 378787.08032243
#Sta/Elev= 30
       0  951.45     7.7  945.32    24.6  940.33    47.6   927.3    97.9  892.74
   104.4  889.65   122.6  887.56   171.8  885.87   286.7  886.62   290.8  886.43
   296.8  884.18   303.1  883.43   314.8884.1875   328.1  889.88   348.3  892.02
   360.6  902.78     373  910.37   397.3  930.28   418.6  943.48   435.2  956.73
   458.1  966.76   486.2  972.93   490.7  975.43   504.8  988.68   529.2 1007.32
   546.6  1014.1   568.3 1018.77   578.4 1024.71   593.6 1035.61   614.5 1047.71
#Mann= 5 ,-1,0
       0      .1       0  276.25     .06       0   296.8    .045       0
   314.8     .06       0  426.25      .1       0
#XS Ineff= 2 , 0
           180.4  897.87
Permanent Ineff=
       F       F
Bank Sta=296.8,314.8
XS Rating Curve= 0 ,0
Exp/Cntr(USF)=0,0
Exp/Cntr=0.3,0.1

Type RM Length L Ch R = 1 ,16006   ,405.7,407.3,408.6
XS GIS Cut Line= 6
1659950.97425726378102.379264012 1659946.7137671378197.933206752
1659941.57007658378287.1069129261659932.37455693378362.512273923
 1659859.0978006378614.5773865881659839.67756385378706.524709255
#Sta/Elev= 30
       0  915.62    22.2  904.77    42.2  899.76    66.2     897    86.2  891.53
   110.3  886.67   126.3  885.19   186.4  883.39   238.8  880.54     288  881.47
   306.1877.8638   308.9  877.38   317.9877.8281   321.4  878.91   329.7  883.87
   342.2  884.64   346.4  885.82     363  899.36   375.5  911.39     388  920.87
   429.7   939.7   458.8  957.67   475.5  964.58     488  967.18   500.5  971.54
   517.1  982.16     548  999.57   574.5 1011.39   594.9 1017.76   617.4 1022.75
#Mann= 5 ,-1,0
       0      .1       0  260.93     .06       0   306.1    .045       0
   317.9     .06       0  465.93      .1       0
Bank Sta=306.1,317.9
XS Rating Curve= 0 ,0
Exp/Cntr(USF)=0,0
Exp/Cntr=0.3,0.1

Type RM Length L Ch R = 1 ,15598   ,596.1,593.1,588.5
XS GIS Cut Line= 6
1659706.48980044378007.2840485461659666.96389759378106.612034159
 1659506.3827616378353.0793159361659491.80273313378403.010642446
1659457.25977078378456.0467365731659390.44143029378546.581154103
#Sta/Elev= 30
       0  955.47    26.9     940    62.1  923.14    78.5  912.36    95.9  898.43
   104.1  895.35   118.8  893.08   142.5  882.26   156.8  878.19   166.3   878.5
   209.1   875.3     260  876.16   289.1  874.91   325.4  875.43     339 872.932
     343  872.69   348.7872.8909   352.6  873.14   362.1  877.63   386.1  878.21
   395.7  880.52   438.1   884.6   474.1  893.02   488.4  899.38   545.3  930.64
   552.1   933.1   566.2  943.18   585.7  954.37   601.6  959.41     629  970.13
#Mann= 5 ,-1,0
       0      .1       0  292.23     .06       0     339    .045       0
   348.7     .06       0  411.13      .1       0
Bank Sta=339,348.7
XS Rating Curve= 0 ,0
Exp/Cntr(USF)=0,0
Exp/Cntr=0.3,0.1

Type RM Length L Ch R = 1 ,15005   ,490.6,496.4,498.3
XS GIS Cut Line= 6
 1659161.1067425377737.1398370121659152.04836167377830.523836583
1659143.43518992377917.6601452531659135.71276443377992.302384421
1659122.99723868378091.4941151741659088.27749184378345.381074592
#Sta/Elev= 30
       0 1003.53    35.6   989.5    51.7  980.87    79.8  967.34   107.9   958.9
     128  952.05   148.1  942.51   156.1  937.95   176.2  929.97   188.3  926.21
   205.3  917.65   236.6  899.94   252.5  892.74   260.7  888.27   280.9  874.94
   288.9  868.68   291.4867.8251   309.1  866.91   315.5 867.774   349.2  870.63
   406.1  871.49   426.1  875.06   450.3   875.5   454.4  876.36   466.5  883.91
   516.2  907.79   535.1  918.19   578.8  940.56   599.7   952.7   612.7  958.32
#Mann= 5 ,-1,0
       0      .1       0   291.4    .045       0   315.5      .1       0
  336.42     .06       0  528.93      .1       0
Bank Sta=291.4,315.5
XS Rating Curve= 0 ,0
Exp/Cntr(USF)=0,0
Exp/Cntr=0.3,0.1

Type RM Length L Ch R = 1 ,14509   ,504,500.1,492.9
XS GIS Cut Line= 6
1658866.30680718377652.5714365841658828.94270867377740.386549667
1658789.65341717377820.3571902511658746.39333309377882.494533166
1658679.93677309 377958.021941171658541.66834883378195.971596509
#Sta/Elev= 30
       0 1005.63    21.7  988.09    56.5  964.67    95.6  951.48   122.3  934.24
   135.7  929.82   151.7  921.34   184.5  899.51   208.8  891.93   234.6  877.38
     249  865.86   257.2  863.59   289.6  864.88   307.1862.1685   312.1  861.79
     320  862.18   331.3  864.36   358.9  864.53   368.5  862.85     441  867.32
   443.8  868.52   471.5  892.44   490.8  906.22   503.8  917.95   531.5  932.48
   558.2  951.02   572.7  956.75   614.6  967.09   627.6  974.63   636.1  981.73
#Mann= 5 ,-1,0
       0      .1       0   307.1    .045       0     320      .1       0
  370.85     .06       0  492.68      .1       0
Bank Sta=307.1,320
XS Rating Curve= 0 ,0
Exp/Cntr(USF)=0,0
Exp/Cntr=0.3,0.1

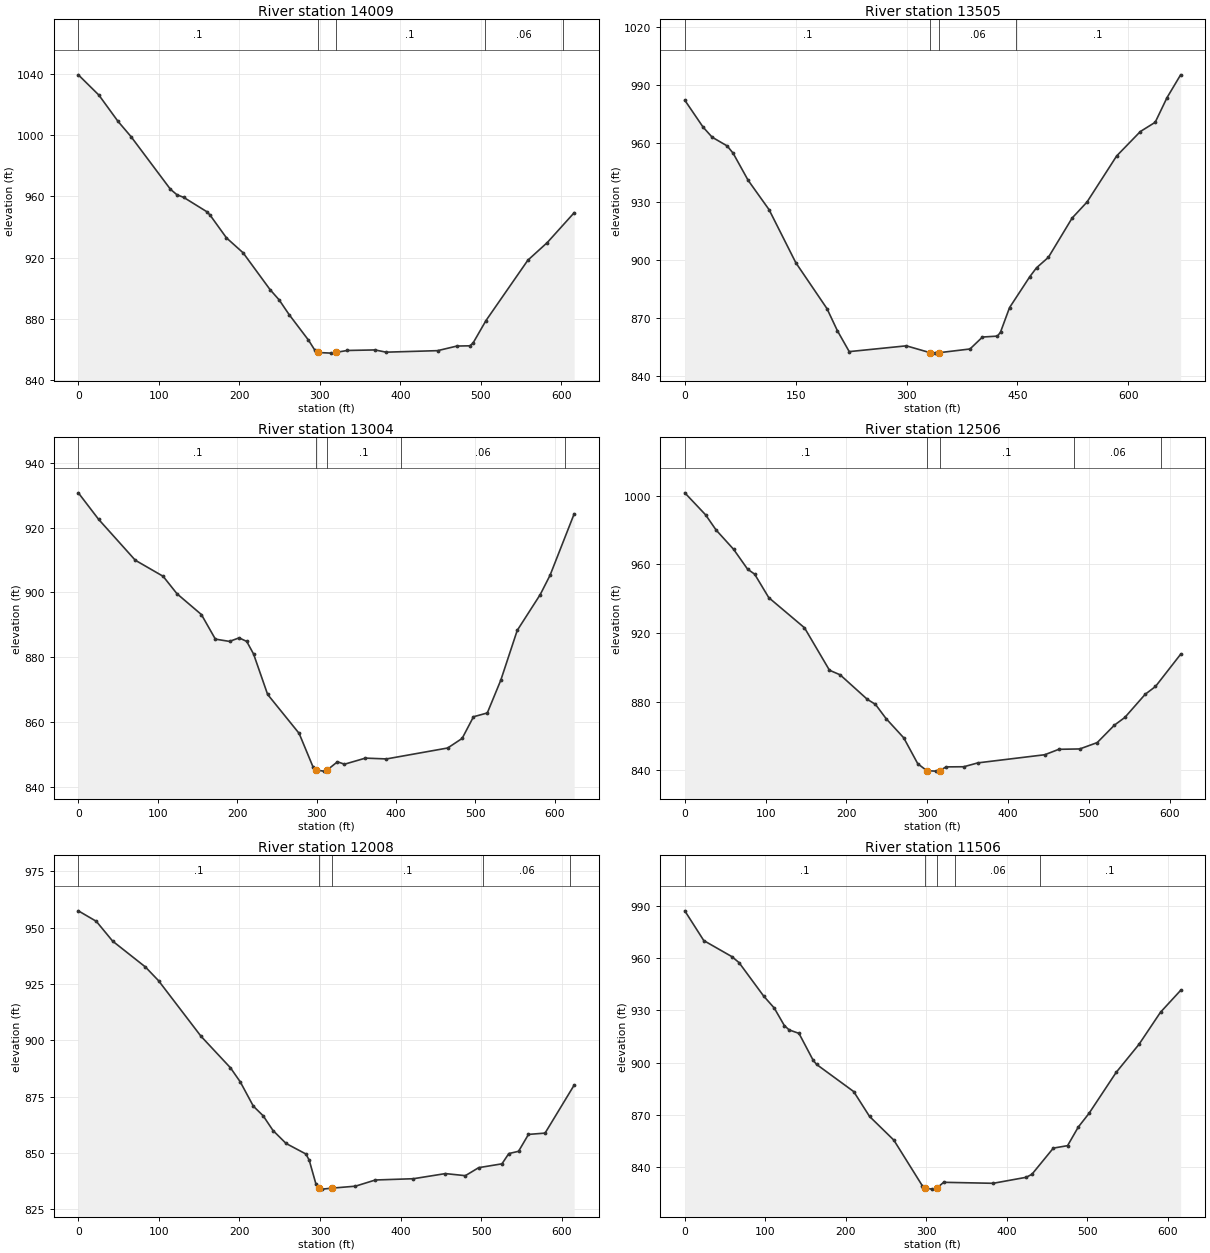
Type RM Length L Ch R = 1 ,14009   ,503.1,503.8,499.4
XS GIS Cut Line= 6
1658314.05988017377472.3861014251658295.58091451377565.249432758
1658260.45565668377726.1618405881658250.68861584377825.876864254
1658244.88777442377988.2735210961658238.65353492378081.860604256
#Sta/Elev= 30
       0 1039.53    25.6 1026.23    49.1 1009.21    65.4  999.13   114.4  964.66
   122.6  961.02   130.8  959.37   159.4  950.03   163.5  947.85     184  932.85
   204.7  923.07   238.2  898.96   249.5  892.24   261.8  882.67   285.9  865.93
   293.9  859.26   297.1 857.858     314  857.43   319.9857.9088   334.1  859.17
   368.5  859.52   382.3  858.06   446.3  859.05   470.3  862.06   486.3  862.22
   490.3  864.02   506.3  878.68   558.4  918.25   582.5  929.77   615.9  949.29
#Mann= 5 ,-1,0
       0      .1       0   297.1    .045       0   319.9      .1       0
  504.58     .06       0  602.08      .1       0
Bank Sta=297.1,319.9
XS Rating Curve= 0 ,0
Exp/Cntr(USF)=0,0
Exp/Cntr=0.3,0.1

Type RM Length L Ch R = 1 ,13505   ,502.3,500.5,494.6
XS GIS Cut Line= 6
1657822.19176942377532.1172811691657850.44171293377726.492876679
1657849.67006092377812.4438202531657806.97001509377919.563356668
1657792.84898034378001.0697553461657778.32374692378190.888929501
#Sta/Elev= 30
       0  982.32    24.8   968.4      37  963.23    57.3  958.73    65.4  954.96
    85.7  940.97     114  925.83   150.2  898.43   192.4  874.71   206.5  863.29
   222.5  852.52   299.8  855.51   331.9851.9649   339.1  851.74   344.3  851.97
   385.9  853.88   402.8  860.05   423.1  860.53   427.2   862.6   439.4  875.23
   466.8   891.2   475.9   895.8     492  901.21   524.1  921.49   544.2  929.73
   584.4  953.58   616.4  966.15   636.5  970.93   652.5  983.66   670.9  995.43
#Mann= 4 ,-1,0
       0      .1       0   331.9    .045       0   344.3     .06       0
  447.77      .1       0
Bank Sta=331.9,344.3
XS Rating Curve= 0 ,0
Exp/Cntr(USF)=0,0
Exp/Cntr=0.3,0.1

Type RM Length L Ch R = 1 ,13004   ,497.5,498.9,497.5
XS GIS Cut Line= 6
1657257.63843659377599.1962152571657362.86361983377832.772847846
1657404.63715833377923.6588209271657436.80769767377992.698709086
1657472.99430509378075.6165222531657499.16649684378173.800052926
#Sta/Elev= 30
       0  930.72    25.5  922.56    71.7  909.95   106.8  904.99   124.3   899.6
     155   893.2   172.6  885.62   190.4  884.92   202.5  886.01   212.1  884.91
   220.7  881.04   238.4  868.58   278.1  856.56   295.5  846.28   299.9  845.27
   308.8  844.93   313.4845.2718   326.4  847.81   335.2  847.06   361.6  848.94
   388.1  848.69   465.2  852.06   483.4  855.01   497.7  861.69   515.1  862.86
   532.1  872.97   552.8  888.31   581.8  899.37   594.2  905.34   624.5  924.23
#Mann= 5 ,-1,0
       0      .1       0   299.9    .045       0   313.4      .1       0
  406.21     .06       0  612.85      .1       0
Bank Sta=299.9,313.4
XS Rating Curve= 0 ,0
Exp/Cntr(USF)=0,0
Exp/Cntr=0.3,0.1

Type RM Length L Ch R = 1 ,12506   ,496,497.6,498.9
XS GIS Cut Line= 6
1656828.74296892 377820.844065921656865.12642634377907.937395677
1656902.38160117377987.1393370031657003.19636017 378215.91086109
 1657036.1388796378297.0130610911657066.67556392378386.005665258
#Sta/Elev= 30
       0 1001.57    25.7  988.78    38.7  979.94    60.4  968.68    77.7  957.13
    86.4  954.24   103.9  940.55   148.1     923     179  898.29   192.2  895.62
   225.9  881.32   235.9  878.42     249  870.16   270.9  858.93   288.3  843.82
   299.6  839.78   310.2  839.55   315.2  839.78   323.3  842.02   345.2   842.1
   362.7  844.36   445.4  849.09   462.8  852.25   488.7  852.47   510.3  856.16
   531.6  866.33   544.5  870.81   569.7   884.3   582.4  888.82   613.5  907.59
#Mann= 5 ,-1,0
       0      .1       0   299.6    .045       0   315.2      .1       0
  481.91     .06       0  589.45      .1       0
Bank Sta=299.6,315.2
XS Rating Curve= 0 ,0
Exp/Cntr(USF)=0,0
Exp/Cntr=0.3,0.1

Type RM Length L Ch R = 1 ,12008   ,503.7,502.4,499.7
XS GIS Cut Line= 6
1656409.28613067377870.5388484151656453.06196176378122.952713668
 1656474.9743195378220.7783054261656494.59567134378293.817529425
1656516.54674293378379.4036443381656538.98895526378471.548145086
#Sta/Elev= 30
       0  957.41    22.3  952.76    42.6  943.97    83.2  932.52    99.5  926.44
   152.2  901.79   188.8  887.78     201  881.52   217.2  870.76   229.4  866.49
   241.6  859.97   257.8  854.23   282.4  849.55   286.5  846.83   294.7  836.43
   298.6834.4111   302.9  833.97   315.2  834.42   343.9  835.28   368.6  838.02
   415.9  838.59   455.5  840.86   480.3  839.94   496.8  843.49   525.7  845.19
   534.2  849.74   546.3  850.75   558.6  858.24   579.2  858.82   615.3   880.1
#Mann= 5 ,-1,0
       0      .1       0   298.6    .045       0   315.2      .1       0
  502.06     .06       0  610.42      .1       0
Bank Sta=298.6,315.2
XS Rating Curve= 0 ,0
Exp/Cntr(USF)=0,0
Exp/Cntr=0.3,0.1

Type RM Length L Ch R = 1 ,11506   ,496.6,500.2,503.5
XS GIS Cut Line= 6
1655926.29168984378154.9936600921655964.45631167378240.603725091
1656072.17886525378479.9825114161656102.94028668378548.383621335
1656141.37820192378628.8824760911656182.70390667378715.255662918
#Sta/Elev= 30
       0  986.95    23.6   969.9    58.6  960.68    67.4  957.28      98  938.12
   111.2  931.23   123.7  921.22   129.7  918.71   141.9  916.73   159.5  901.34
   163.8  898.93   209.9  883.39   229.6  869.14   259.8  855.56   295.4  829.26
   298.9828.0013   307.3  827.48     313  827.99   321.7  831.39   383.2  830.82
   424.3  834.26   431.4  835.99     458  850.98   475.7  852.39     489  863.04
   502.3  870.85     536  894.32   564.4  910.41   591.2  928.85   616.2  941.37
#Mann= 5 ,-1,0
       0      .1       0   298.9    .045       0     313      .1       0
  336.23     .06       0  441.23      .1       0
Bank Sta=298.9,313
XS Rating Curve= 0 ,0
Exp/Cntr(USF)=0,0
Exp/Cntr=0.3,0.1