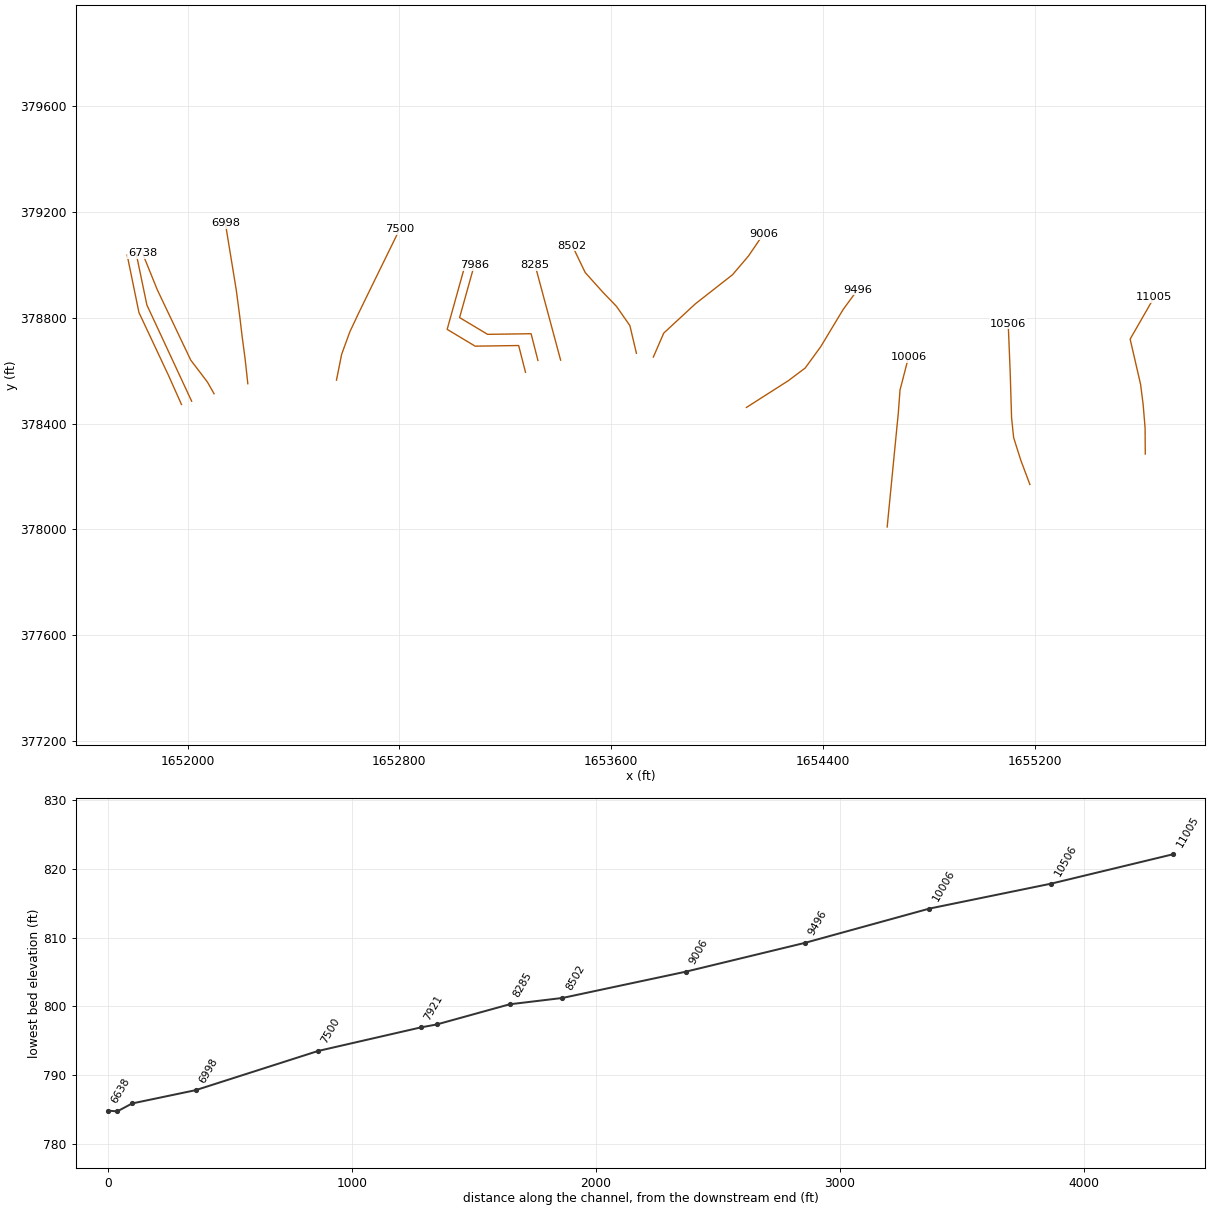
HEC-RAS study RICHWDRN.prj: RICHWDRN

--- RICHWDRN.g01 (geometry) --- (continued)

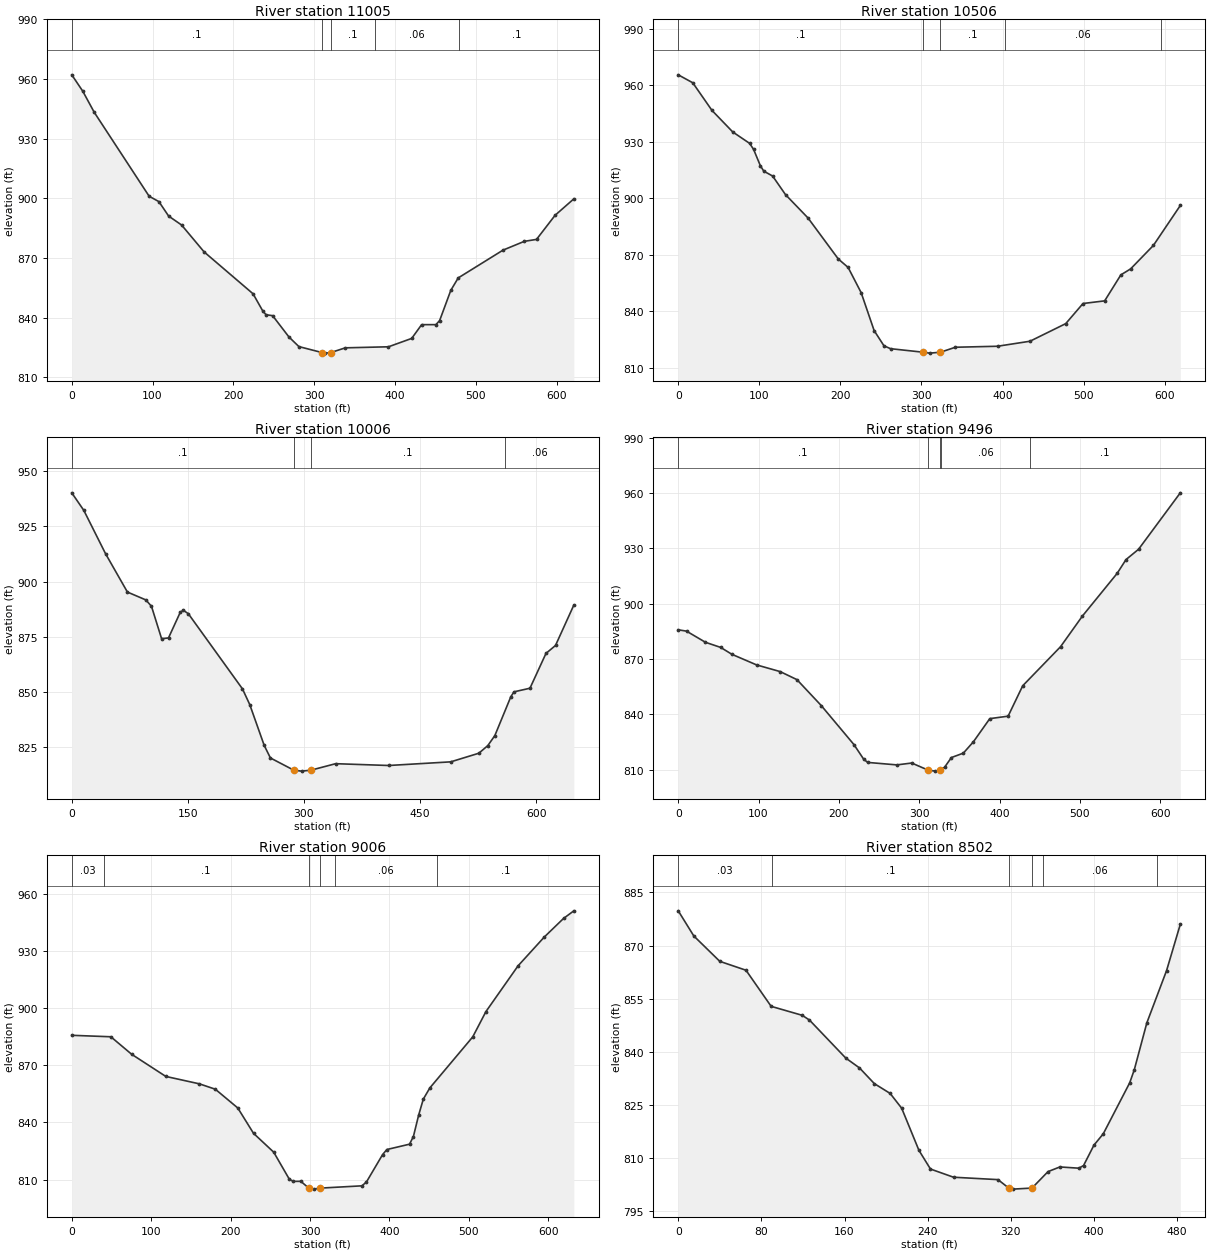
Type RM Length L Ch R = 1 ,11005   ,502,499.8,497.3
XS GIS Cut Line= 6
1655618.44683309378284.7460252491655617.77229376378383.067350924
1655610.34120625378472.5835760831655600.69719668378548.159212336
1655561.26059575 378719.050274761655651.67777624378876.681890623
#Sta/Elev= 30
       0  962.13    13.6   953.9    27.8  943.28    95.8  901.02   107.8  898.36
   119.9  891.07   135.9  886.58   163.8  873.04   224.4  851.96   236.5  843.25
   240.5  841.43   248.6  840.96   268.8  830.24   281.1  825.41   309.9  822.39
     314  822.12   320.3822.3784   338.6  824.78     392  825.31   420.7  829.52
     433  836.44   450.7  836.45   455.3  838.51   469.1  853.69   478.3  859.96
   533.7  873.93   560.1  878.36   575.2  879.33   598.2  891.47   621.4  899.74
#Mann= 5 ,-1,0
       0      .1       0   309.9    .045       0   320.3      .1       0
  374.75     .06       0  479.72      .1       0
Bank Sta=309.9,320.3
XS Rating Curve= 0 ,0
Exp/Cntr(USF)=0,0
Exp/Cntr=0.3,0.1

Type RM Length L Ch R = 1 ,10506   ,503.3,500,502
XS GIS Cut Line= 6
1655182.39750834378169.5756519291655148.16430908 378260.90552175
1655120.97177817378346.962764338 1655113.2470561378421.685383916
1655107.86452092378596.602685004 1655100.4691945378777.713543251
#Sta/Elev= 30
       0  965.52    17.9  961.31    41.6  946.64    67.2  935.22      88  929.16
    92.9     926   101.3  917.28   105.5  914.41   116.4  911.82   132.3  901.95
   160.1  889.54   197.4   867.8   209.5  863.33   225.6  849.93   241.6  829.81
   253.7  821.75   261.8  820.21   302.4818.3145     310  817.85   323.2818.3022
   341.8  820.97   393.8   821.5   433.8  824.16   477.9   833.5   499.2  844.18
   525.9  845.58   545.9  859.38   557.9  862.54     586     875   619.2  896.19
#Mann= 5 ,-1,0
       0      .1       0   302.4    .045       0   323.2      .1       0
  402.91     .06       0  595.41      .1       0
Bank Sta=302.4,323.2
XS Rating Curve= 0 ,0
Exp/Cntr(USF)=0,0
Exp/Cntr=0.3,0.1

Type RM Length L Ch R = 1 ,10006   ,521.8,509.3,508.9
XS GIS Cut Line= 6
1654643.14038476378009.0149494261654652.24371301378102.321849421
 1654677.7338195378363.5814975051654685.07960534378438.220783919
1654691.63372609378526.3731666651654723.86069576378651.450672418
#Sta/Elev= 30
       0  940.24    15.6  932.27    43.7  912.64    71.9  895.31    95.7  891.75
     103  888.86   116.1  874.16     125  874.54   140.2  886.14   144.2  887.05
   150.6  885.51   220.6  851.45     230  844.35   248.7  825.84   256.7  820.18
     287 814.636   296.9  814.22     309  814.64     341  817.59   409.5  816.77
   489.7  818.42     526  822.32   537.6  825.77   546.7   830.3   567.3  847.85
   571.4  850.12   592.1  851.76   612.8  867.53   625.1  871.12   648.8  889.42
#Mann= 4 ,-1,0
       0      .1       0     287    .045       0     309      .1       0
  559.65     .06       0
Bank Sta=287,309
XS Rating Curve= 0 ,0
Exp/Cntr(USF)=0,0
Exp/Cntr=0.3,0.1

Type RM Length L Ch R = 1 ,9496    ,491.4,489.9,487.7
XS GIS Cut Line= 6
1654111.35568717378460.8342557551654270.47249493378562.493173167
1654333.33358967378609.7791678461654392.45355017378691.111026168
1654476.41598067378830.5815477521654532.06088251378906.546618924
#Sta/Elev= 30
       0  885.87    10.3  885.15    33.9   879.1    52.8  876.33    66.9  872.57
    97.6  866.83   126.9  863.22   147.8  858.85     178  844.83   218.8  823.62
   230.9  815.71   235.9  813.97   272.2  812.63   290.7  813.64   311.2809.7764
   320.1  809.25   325.9  809.78   331.6  811.35   340.1  816.61     355  819.02
   367.5  825.16   387.9  837.71   410.7  839.05   428.9  855.54     476  876.71
   503.3  893.38   546.5  916.49   557.5  923.95   573.1  929.53   625.1  960.14
#Mann= 5 ,-1,0
       0      .1       0   311.2    .045       0   325.9      .1       0
  327.49     .06       0  438.04      .1       0
Bank Sta=311.2,325.9
XS Rating Curve= 0 ,0
Exp/Cntr(USF)=0,0
Exp/Cntr=0.3,0.1

Type RM Length L Ch R = 1 ,9006    ,496.5,504.8,524.9
XS GIS Cut Line= 6
1653759.55324118378651.3591371771653798.78971125378741.784153178
1653918.01650693378852.1743523331654058.84398118378962.507793084
 1654118.8317221379033.0151980071654174.95693792379115.265689671
#Sta/Elev= 30
       0  885.73    49.2  884.96    75.4  875.78   118.4  864.16   160.7  860.27
   180.7  857.46     209  847.62   228.8  834.33   254.3   824.4     274  810.17
   279.1  809.11   288.4  809.14   298.4  805.58   304.8  805.05   312.5 805.574
   365.3  806.78     371   808.8   391.3  823.15   396.7  825.82   425.2  828.62
   430.1  832.62   436.7  843.86   442.6  852.28   450.8  858.13   504.8  884.89
   521.4  898.16   561.9  922.18   594.9  937.28   619.1  947.01   632.1  951.02
#Mann= 6 ,-1,0
       0     .03       0      40      .1       0   298.4    .045       0
   312.5      .1       0  331.07     .06       0  459.98      .1       0
Bank Sta=298.4,312.5
XS Rating Curve= 0 ,0
Exp/Cntr(USF)=0,0
Exp/Cntr=0.3,0.1

Type RM Length L Ch R = 1 ,8502    ,217.9,216.5,209
XS GIS Cut Line= 6
1653695.56649251378665.5746599291653670.81621392378770.215198666
1653620.16178767378842.9453681711653568.19994934378897.028593332
1653501.93180666378970.8681849981653453.10798625 379072.50324451
#Sta/Elev= 30
       0  879.79      15  872.69      40  865.53    65.2  863.02    89.4  852.83
   119.3   850.3   126.3  848.95   161.2  838.23   174.4  835.45   188.7  831.02
   203.9  828.25     215  824.08   231.6  812.19   242.7  806.91   264.9   804.6
   307.7  803.92   318.1801.5208   321.9  801.24   340.4  801.54   355.8  806.18
   367.2   807.5   385.5  807.15     390   807.9     400  813.65     409  816.87
   434.4  831.24   438.8  834.91   450.9  848.18   469.9  862.94   483.1     876
#Mann= 6 ,-1,0
       0     .03       0      90      .1       0   318.1    .045       0
   340.4      .1       0  351.16     .06       0  460.38      .1       0
Bank Sta=318.1,340.4
XS Rating Curve= 0 ,0
Exp/Cntr(USF)=0,0
Exp/Cntr=0.3,0.1

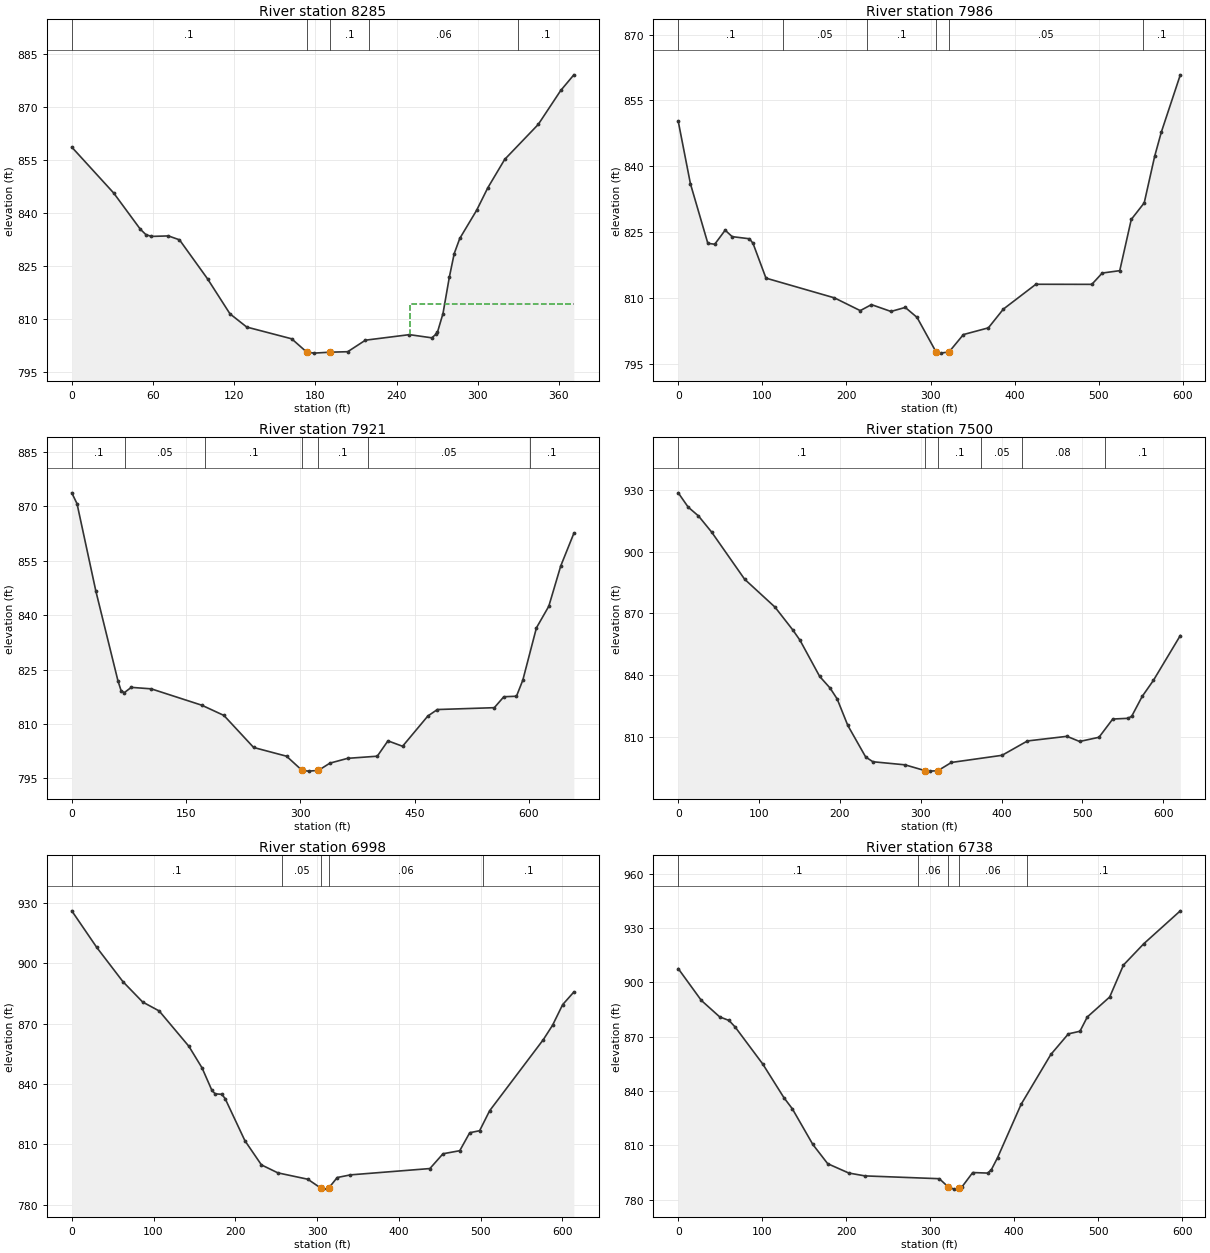
Type RM Length L Ch R = 1 ,8285    ,297.3,299,306.8
XS GIS Cut Line= 2
1653409.13862286378639.6317567681653312.82164728378997.883922052
#Sta/Elev= 30
       0  858.73      31   845.7    50.6  835.48    54.8  833.91    58.9  833.41
    71.4  833.55    79.6  832.44   100.3   821.4   116.9  811.46   129.3  807.71
   162.5  804.38   173.6800.6247     179  800.32   190.9  800.59   203.9  800.72
     217  803.99   249.5  805.56     266  804.66   269.3  805.72   270.2  806.22
   274.3  811.54     279  821.86   282.6  828.54   286.7  832.83   299.2  840.84
   307.4  847.18   319.9  855.24   344.7  865.16   361.3  874.78     371  879.22
#Mann= 5 ,-1,0
       0      .1       0   173.6    .045       0   190.9      .1       0
     220     .06       0     330      .1       0
#XS Ineff= 1 ,-1
  250.22370.9738  814.12
Permanent Ineff=
       F
Bank Sta=173.6,190.9
XS Rating Curve= 0 ,0
Exp/Cntr(USF)=0,0
Exp/Cntr=0.3,0.1

Type RM Length L Ch R = 1 ,7986    ,64.3,65.4,65.4
XS GIS Cut Line= 5
1653323.39302264378638.4571595041653297.55188285378739.472524142
  1653133.108266378737.1233296161653027.39451231 378800.55158183
1653082.60058368378997.883922052
#Sta/Elev= 30
       0  850.25    14.5     836    35.2  822.42    43.4  822.22    55.8  825.42
    64.1  823.95    84.7  823.46    88.9  822.42   104.3  814.49   185.7  809.99
   216.4  807.08   229.7  808.45   252.9  806.89   269.9  807.81   283.9  805.54
   306.5  797.67   311.9  797.39     322  797.67     339  801.62   368.7  803.15
   386.5  807.42   425.2  813.09   491.7  813.07   504.1  815.65   524.9  816.19
   538.6  827.87     554  831.65   566.4  842.26   574.3  847.76   596.9  860.84
#Mann= 6 ,-1,0
       0      .1       0  124.27     .05       0  224.27      .1       0
   306.5    .045       0     322     .05       0  552.01      .1       0
Bank Sta=306.5,322
XS Rating Curve= 0 ,0
Exp/Cntr(USF)=0,0
Exp/Cntr=0.3,0.1

Type RM Length L Ch R = 1 ,7921    ,429.9,420.7,401.5
XS GIS Cut Line= 5
1653276.40913212378593.8224635021653250.56799232378694.837828139
1653086.12437547378692.4886336131652980.41062178378755.916885827
1653052.06105484379013.153686474
#Sta/Elev= 30
       0  873.77     6.9  870.77    31.7  846.57    60.6   821.9    64.7   819.2
    68.9  818.61    78.1  820.08   104.3  819.67   170.7  815.15   199.7  812.33
   238.7  803.49   281.9  801.08   302.3  797.16     311  796.96   323.7797.1617
   338.8  799.16   362.1  800.49     401  801.08     415  805.32   434.2  803.82
   467.4  812.18   479.9  813.96   554.6  814.47   567.1  817.49   583.7  817.63
     592  822.06   609.9  836.51   626.1  842.46   641.8  853.59     659  862.59
#Mann= 7 ,-1,0
       0      .1       0      70     .05       0  174.27      .1       0
   302.3    .045       0   323.7      .1       0  388.73     .05       0
  602.01      .1       0
Bank Sta=302.3,323.7
XS Rating Curve= 0 ,0
Exp/Cntr(USF)=0,0
Exp/Cntr=0.3,0.1

Type RM Length L Ch R = 1 ,7500    ,495.9,501.7,504.8
XS GIS Cut Line= 6
1652562.12650217378563.9984195081652581.62875976 378661.55662334
1652612.50271375 378746.296283261652644.49280725378814.362748176
1652688.23418958378904.289077505 1652800.8714315379134.456268087
#Sta/Elev= 30
       0  928.45    12.3  921.52      25  917.26    41.3  909.43    82.1  886.58
   119.7  873.05   141.8  861.94   150.6     857     175  839.43   187.8  833.83
   196.6  828.54   209.8  815.67   231.9  800.38   240.8  798.09   280.6  796.59
   305.6 793.745   311.8  793.54   321.2793.7582     338  797.75   400.6  801.21
     432  808.17   480.9  810.41   496.5  807.91   520.5  809.95   537.5  818.79
   556.7  819.15   561.1  820.25   573.9  829.73   587.8  837.52   621.1  859.27
#Mann= 6 ,-1,0
       0      .1       0   305.6    .045       0   321.2      .1       0
  374.89     .05       0  424.89     .08       0  527.39      .1       0
Bank Sta=305.6,321.2
XS Rating Curve= 0 ,0
Exp/Cntr(USF)=0,0
Exp/Cntr=0.3,0.1

Type RM Length L Ch R = 1 ,6998    ,259,260.3,262.6
XS GIS Cut Line= 6
1652227.16063668378550.3508090081652216.92706133378644.114072919
1652205.40346234378731.2471007561652196.46614426378806.105218753
1652183.36348018378905.3927498461652142.10043934379158.180958167
#Sta/Elev= 30
       0  925.93    30.6  907.75    62.6  890.77    86.7  880.68   106.9  876.25
   143.2  858.71   159.3     848   171.4   836.8   175.4  835.13   183.5  834.88
   187.5  832.79   211.7  811.88   231.9  799.88     252  795.92   288.6  792.76
   304.4  788.39   312.5  787.85   314.2788.4057   324.6  793.61   340.7  794.92
   437.9  798.06   453.9  805.39   474.4  806.92   486.6  815.83   498.7  816.84
   510.9  826.72   576.6  862.04   587.9  869.19   600.2  879.38   613.9  885.65
#Mann= 5 ,-1,0
       0      .1       0   257.6     .05       0   304.4    .045       0
   314.2     .06       0  502.72      .1       0
Bank Sta=304.4,314.2
XS Rating Curve= 0 ,0
Exp/Cntr(USF)=0,0
Exp/Cntr=0.3,0.1

Type RM Length L Ch R = 1 ,6738    ,61,61,60.9
XS GIS Cut Line= 5
 1652099.5745149378512.6433227411652074.55008619378556.733982839
1652011.34423065378639.8816778391651884.69694109378906.325429099
1651829.33200577379043.353644033
#Sta/Elev= 30
       0  907.55    27.5  890.01    49.4  880.91    60.5  878.95    67.9  875.27
   100.7  854.89   125.8   836.4   135.9  830.21   160.3  810.55     178  799.94
   203.1   794.8   222.3  793.22   310.9  791.67   321.6   787.1   328.6  785.92
   334.3786.3841   338.2  787.35   350.7  795.07   368.5  794.77   372.9  796.65
   380.2  803.21   408.3  832.69   443.7  860.18   464.6  871.56   478.4     873
   487.1  880.86   513.8  891.89   530.2  909.52   554.4  921.27   597.9  939.42
#Mann= 5 ,-1,0
       0      .1       0  285.14     .06       0   321.6    .045       0
   334.3     .06       0  415.14      .1       0
Bank Sta=321.6,334.3
XS Rating Curve= 0 ,0
Exp/Cntr(USF)=0,0
Exp/Cntr=0.3,0.1

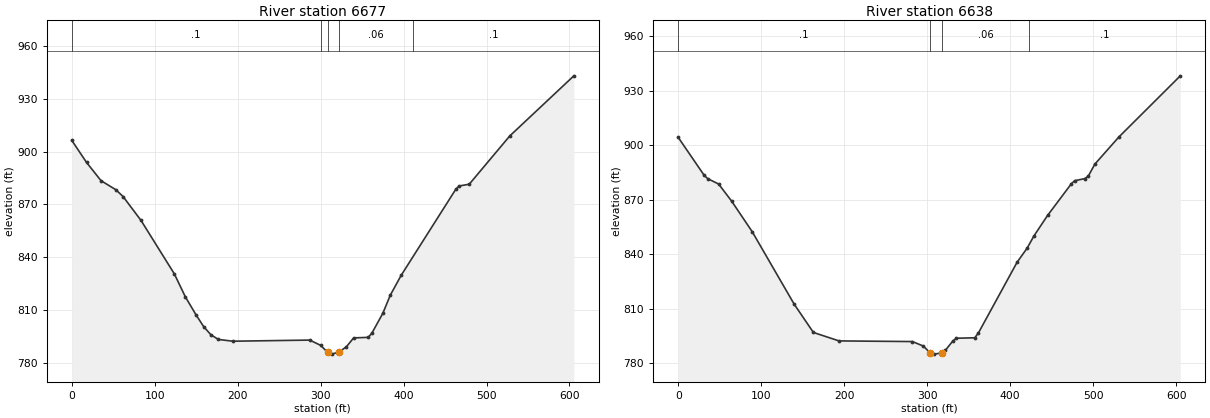
Type RM Length L Ch R = 1 ,6677    ,38.9,38.9,38.9
XS GIS Cut Line= 3
  1652014.852036378484.3983465221651845.68140028378848.115213321
1651804.15769878379048.044146445
#Sta/Elev= 30
       0  906.39    17.8  893.83    35.3  883.43    53.1  878.31    61.9   874.4
    83.5  860.82   123.7   830.4   136.9  817.39   150.1  806.89     159  800.43
   167.8  795.75   176.8  793.12   194.3  792.12   286.9  792.76   300.1  789.75
   308.4785.7916   313.4  784.77   322.1785.9644     331   788.9   339.8     794
   357.5  794.31   361.9  796.78   375.1  808.06     384  818.31   397.2  829.66
   462.8  878.43   466.9  880.42   479.2  881.44     528  908.87   605.3   943.1
#Mann= 5 ,-1,0
       0      .1       0     300     .06       0   308.4    .045       0
   322.1     .06       0  411.13      .1       0
Bank Sta=308.4,322.1
XS Rating Curve= 0 ,0
Exp/Cntr(USF)=0,0
Exp/Cntr=0.3,0.1

Type RM Length L Ch R = 1 ,6638    ,138.6,138.3,137.8
XS GIS Cut Line= 4
1651976.40416424 378472.095027561651928.72880327378578.980111038
1651815.69206031378819.6637882221651771.09252907379037.278742353
#Sta/Elev= 30
       0  904.23    31.1  883.46    35.5  881.52    48.7  878.55    64.2  869.24
    89.1  852.34   139.7  812.42   162.9  796.81   193.8  792.16   282.3   791.8
   295.5  789.29   303.3785.6887   308.8  784.88   317.5 785.596     322  787.01
   330.9   792.1   335.3  793.63   357.4  793.88   361.8  796.57   408.3  835.41
   420.6  843.33   428.7  849.98   445.1  861.24   473.7  878.66   477.7  880.38
     490  881.54   494.1  882.86   502.2  889.57   530.8  904.34   605.1  938.15
#Mann= 4 ,-1,0
       0      .1       0   303.3    .045       0   317.5     .06       0
  422.94      .1       0
Bank Sta=303.3,317.5
XS Rating Curve= 0 ,0
Exp/Cntr(USF)=0,0
Exp/Cntr=0.3,0.1