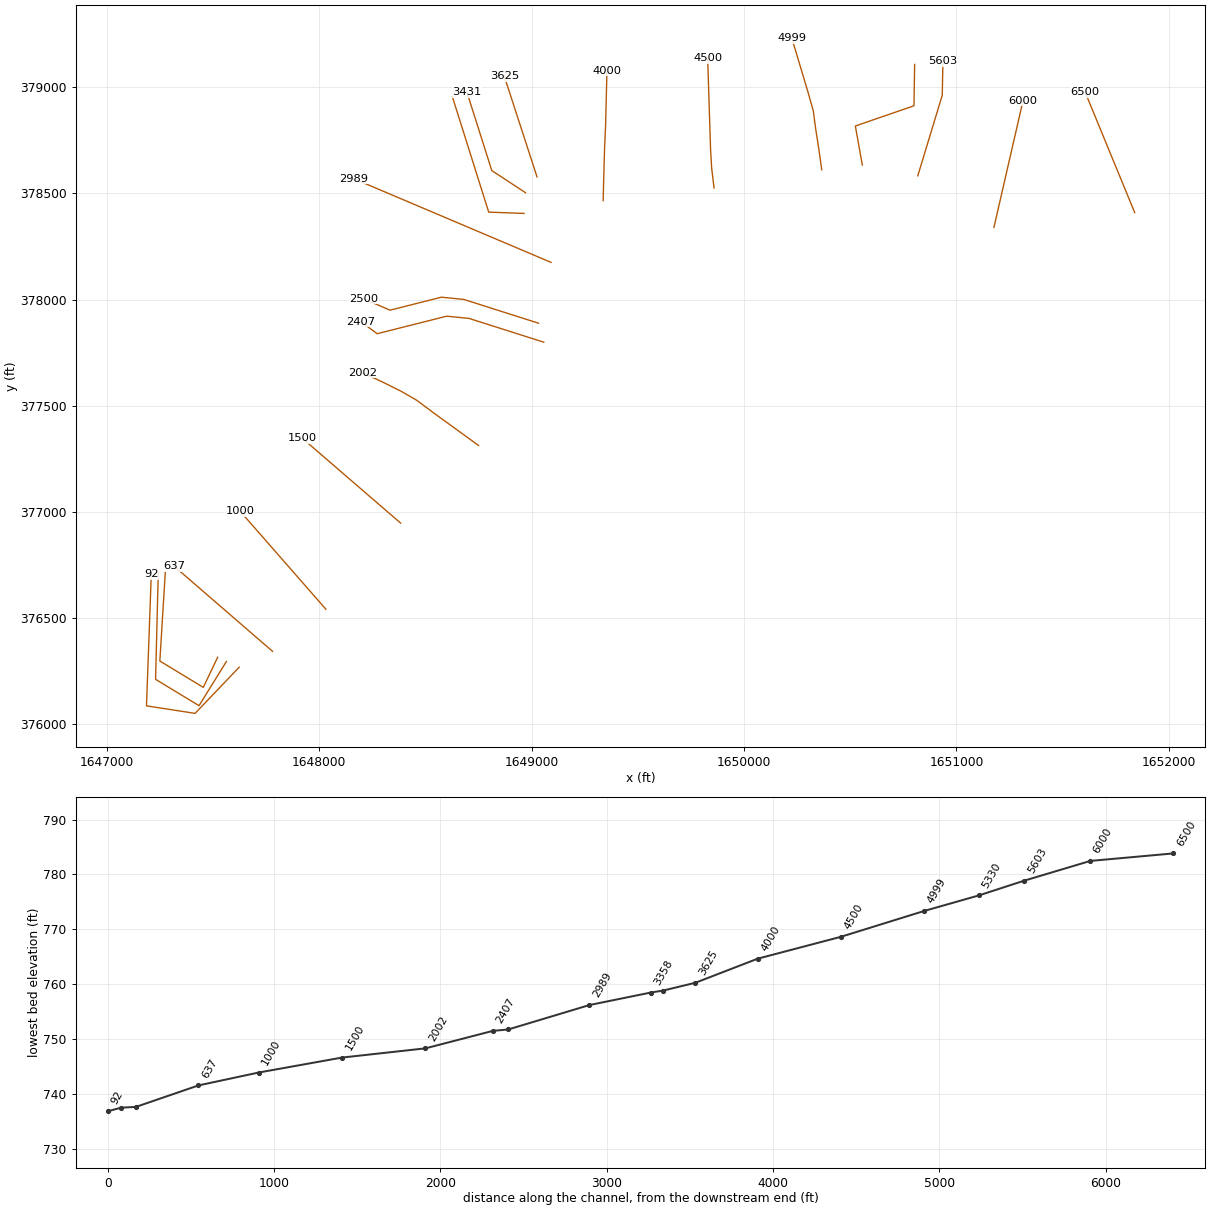
HEC-RAS study RICHWDRN.prj: RICHWDRN

--- RICHWDRN.g01 (geometry) --- (continued)

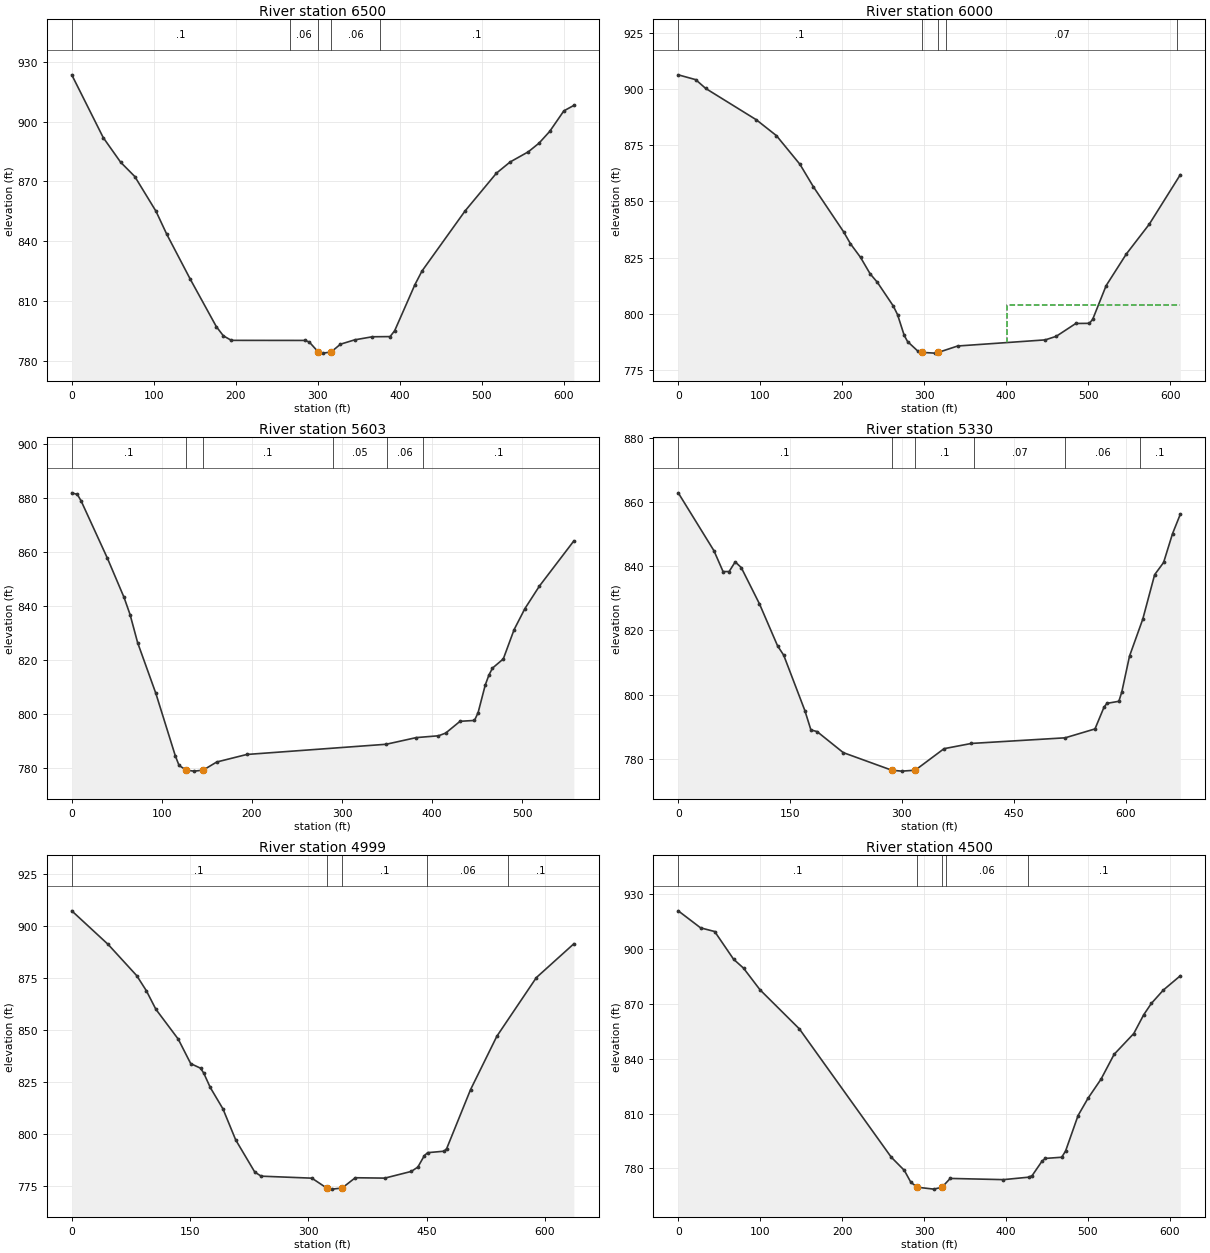
Type RM Length L Ch R = 1 ,6500    ,504.5,500,493.3
XS GIS Cut Line= 6
1651839.13779068378409.439673498 1651770.1648315378577.053183421
1651741.62453426378646.4106562581651703.57014842378738.886849254
1651675.02985117378808.2443220911651606.05656393   378975.857832
#Sta/Elev= 30
       0   923.5    38.4  891.99    59.6  879.65    76.9  872.46   102.8     855
   115.8  843.57   144.6  820.92   176.4  797.11     185   792.5   194.7  790.25
   284.5  790.21   289.7  789.43   300.9784.3434   306.1  783.84   316.2  784.36
   327.8  788.32   345.1   790.5   366.7  792.05   388.3  792.14   393.9  795.07
   418.6  818.18   427.2  825.01   479.7  855.14   518.1  874.17   534.8  879.77
     557  884.88     570   889.2     583  895.08   600.3  905.41   612.5  908.15
#Mann= 5 ,-1,0
       0      .1       0  266.25     .06       0   300.9    .045       0
   316.2     .06       0  376.25      .1       0
Bank Sta=300.9,316.2
XS Rating Curve= 0 ,0
Exp/Cntr(USF)=0,0
Exp/Cntr=0.3,0.1

Type RM Length L Ch R = 1 ,6000    ,396.8,396.9,395.6
XS GIS Cut Line= 6
1651176.28576992378339.7915188371651233.62719068378589.543315917
1651256.00411442378687.0076879261651272.78721733378760.105638832
1651292.36690259378845.3869643361651313.34586325378936.759485006
#Sta/Elev= 30
       0  906.26    21.3  904.11    33.6  900.18    95.2  886.28   119.8  879.21
   148.5  866.44   164.9  856.45   201.9  836.35   210.1  831.12   222.4  825.06
   234.1  817.75   242.9  813.98   262.3  803.46   267.5  799.64   275.7  790.34
   279.8   787.6   292.2  783.41   297.2782.8127   312.7  782.47   317.4782.8105
   340.9  785.64   447.7  788.36   461.1  789.94     485  795.66   501.5  795.72
   505.6   797.5     522  812.48   546.6  826.54   574.6   839.8   612.5  861.83
#Mann= 5 ,-1,0
       0      .1       0   297.2    .045       0   317.4      .1       0
  326.25     .07       0  608.75      .1       0
#XS Ineff= 2 , 0
                          401.65          803.68
Permanent Ineff=
       F       F
Bank Sta=297.2,317.4
XS Rating Curve= 0 ,0
Exp/Cntr(USF)=0,0
Exp/Cntr=0.3,0.1

Type RM Length L Ch R = 1 ,5603    ,281.4,273,255.6
XS GIS Cut Line= 3
1650817.68723309378582.6156311921650932.91522461378962.128006941
1650936.08663723379122.812912551
#Sta/Elev= 30
       0  881.96     6.2  881.36    10.4  878.95    39.6   857.7      58  843.24
    64.7  836.88    73.1  826.47    93.3   807.7   114.9  784.59   119.1  780.97
   127.3779.2043   135.8  778.88   145.7779.2269   160.9  782.26   194.3  785.05
     349  788.83   382.4   791.3     407  791.97     415  792.96     431  797.34
     447  797.65     451  800.52     459  810.82     463  814.44     467  817.04
     479  820.44     491   831.3     503  839.09   519.1  847.43   557.3  864.15
#Mann= 6 ,-1,0
       0      .1       0   127.3    .045       0   145.7      .1       0
     290     .05       0     350     .06       0     390      .1       0
Bank Sta=127.3,145.7
XS Rating Curve= 0 ,0
Exp/Cntr(USF)=0,0
Exp/Cntr=0.3,0.1

Type RM Length L Ch R = 1 ,5330    ,317.3,330.9,353.6
XS GIS Cut Line= 4
1650556.57426148378633.3582329641650523.80299783378817.300164385
1650799.71589496378912.4425427071650802.88730758379106.955849497
#Sta/Elev= 30
       0  862.83    47.9   844.8    60.1  838.32    68.2  838.32    76.4  841.33
    84.5  839.56   108.9  828.27   133.2  815.19   141.4  812.29   169.8  795.03
   177.9  789.01   186.1  788.51   221.3  781.95   286.4776.4656   299.7  776.19
   317.7  776.47   356.4  783.18   393.1  784.81   518.8  786.56   558.8  789.33
   570.8  796.05   574.8  797.29   590.8  797.93   594.8   800.9   605.1     812
   622.8  823.46   638.8  837.35   650.8  841.15   662.8  850.14   673.2  856.17
#Mann= 6 ,-1,0
       0      .1       0   286.4    .045       0   317.7      .1       0
  396.84     .07       0  518.69     .06       0  618.69      .1       0
Bank Sta=286.4,317.7
XS Rating Curve= 0 ,0
Exp/Cntr(USF)=0,0
Exp/Cntr=0.3,0.1

Type RM Length L Ch R = 1 ,4999    ,501.7,499.2,495
XS GIS Cut Line= 6
1650365.50327076378610.9366458361650351.11287959378713.157241926
1650336.26185942378808.5179435911650325.73268101378888.253020346
1650298.52505825378984.5891137571650224.89003493379230.031208172
#Sta/Elev= 30
       0  907.07    46.1  890.93    82.4   875.9    94.5  868.71   106.6  859.78
     135  845.41   150.8  833.65   163.3  831.44   167.4  829.02   175.5  822.24
   191.7  811.87   207.8  797.01     232  781.54   240.1  779.57   304.4  778.61
   323.2773.8666   330.3  773.34   342.8  773.89   359.4  778.81   396.9  778.63
   430.4  781.85   438.7  783.92     447  789.44   451.2  790.86   472.1  791.57
   475.3  792.84   505.5  821.12   538.9  846.81     589     875   636.5  891.23
#Mann= 5 ,-1,0
       0      .1       0   323.2    .045       0   342.8      .1       0
  450.27     .06       0  552.77      .1       0
Bank Sta=323.2,342.8
XS Rating Curve= 0 ,0
Exp/Cntr(USF)=0,0
Exp/Cntr=0.3,0.1

Type RM Length L Ch R = 1 ,4500    ,500.1,499.8,497.8
XS GIS Cut Line= 6
1649858.44063659378525.4040085081649847.16802134378618.839845255
1649842.11389759378706.2189355941649839.72184201378781.172197759
 1649836.4718485378881.1195044221649828.29863651379137.253834665
#Sta/Elev= 30
       0  920.84    27.3  911.53    44.5  909.52    67.6  894.35    79.7   889.5
    99.8  877.67   147.9  856.27     260  786.14     276   778.9     284  772.35
     292  769.68     312  768.65     322769.6909     332   774.5     397  773.84
   428.1   775.2   432.1   776.1   444.1  783.95   448.1  785.45   468.1  786.08
   472.8  789.44   488.1  808.91   500.1  818.25   516.1  828.78   532.1  842.36
   556.1  853.74   568.2  863.98   577.5  870.17   592.2  877.52   612.9  885.32
#Mann= 5 ,-1,0
       0      .1       0     292    .045       0     322      .1       0
  326.63     .06       0  426.63      .1       0
Bank Sta=292,322
XS Rating Curve= 0 ,0
Exp/Cntr(USF)=0,0
Exp/Cntr=0.3,0.1

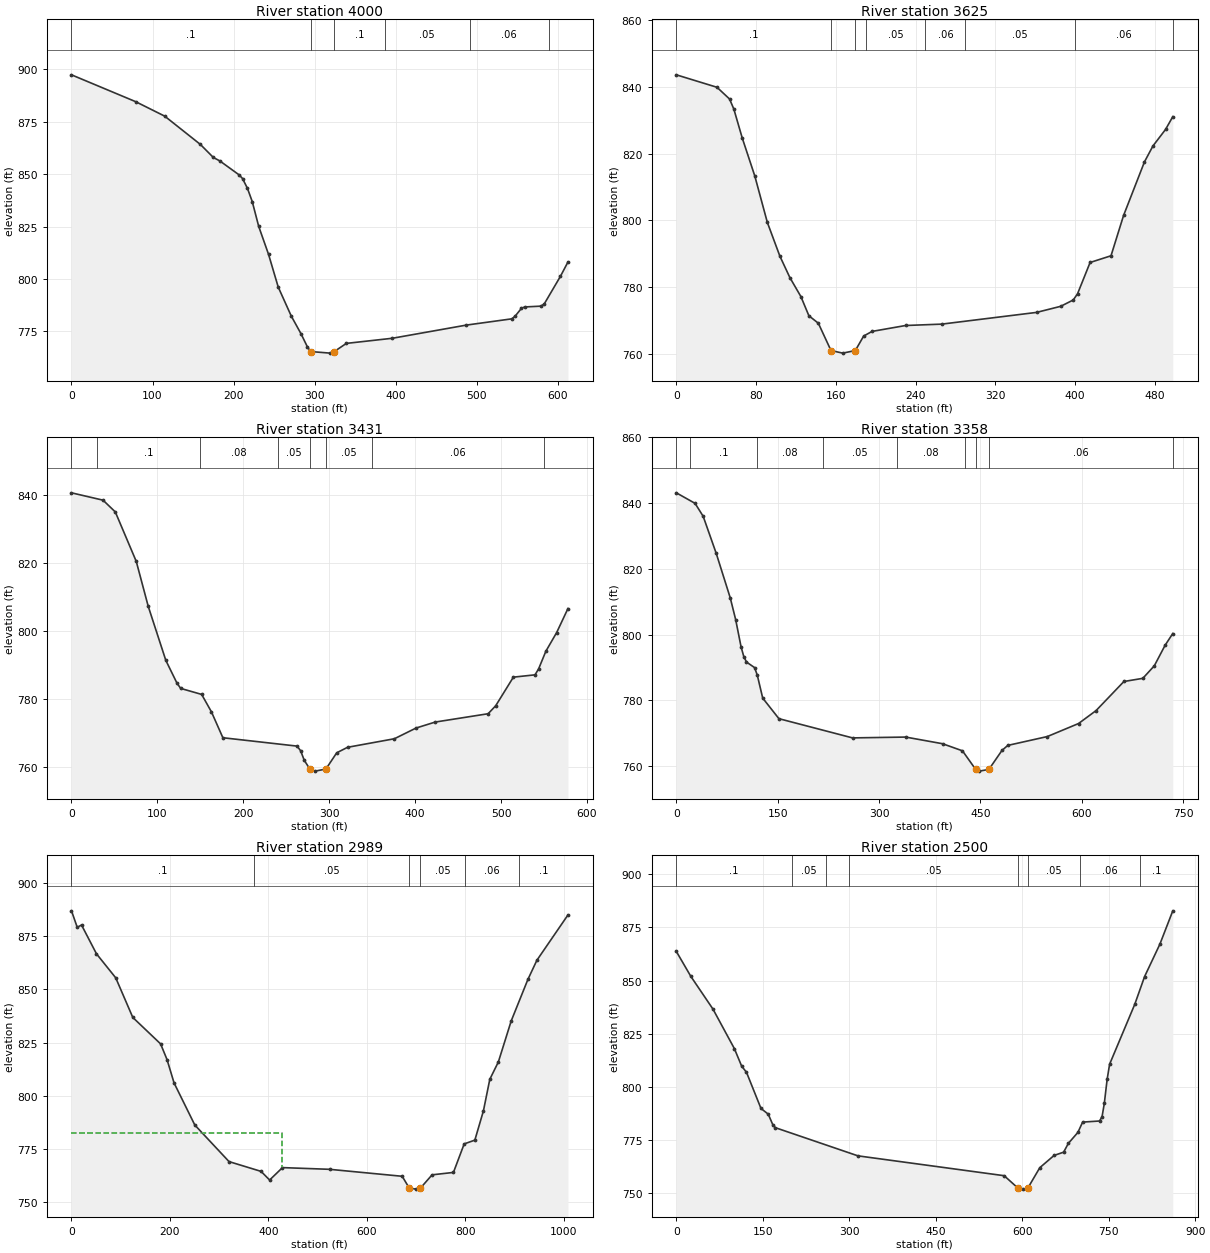
Type RM Length L Ch R = 1 ,4000    ,371.4,375.2,380.8
XS GIS Cut Line= 6
1649336.29109034378465.5773565021649338.69856584378559.322247759
1649341.05584459378646.8119021651649343.31338601378721.791739091
1649347.82617226378821.6904894261649354.11979485379077.821538836
#Sta/Elev= 30
       0  897.39      79  884.62     115  877.69     159   864.2     175  857.98
     183  856.34     207  849.62     211  847.94   217.1  843.24     223  836.96
     231  825.08   243.1   811.8   255.1  796.13   271.2  782.31   283.1  773.96
   291.1  767.61   295.1  765.42   319.1  764.67   324.2765.4171   339.1  769.31
   395.9  771.76   487.2  778.04   543.2  781.02   547.2  782.23   555.2  786.07
   559.2  786.69   579.2  787.08   583.2  788.09   603.2  801.27   612.5  808.12
#Mann= 6 ,-1,0
       0      .1       0   295.1    .045       0   324.2      .1       0
  386.31     .05       0  491.31     .06       0  588.79      .1       0
Bank Sta=295.1,324.2
XS Rating Curve= 0 ,0
Exp/Cntr(USF)=0,0
Exp/Cntr=0.3,0.1

Type RM Length L Ch R = 1 ,3625    ,194.6,194,193.8
XS GIS Cut Line= 2
1649024.86406183 378577.705707181648870.86130954379051.459936683
#Sta/Elev= 30
       0  843.58    40.8  839.85    53.4  836.34    57.7  833.33    66.1   824.7
    78.7  813.33    91.3  799.42   103.9  789.31   113.9  782.91     125   777.2
     133  771.47   142.5  769.23   155.2  761.05     167  760.28   179.6  761.05
     188   765.4   196.4  766.78   230.1  768.55   266.3  768.96   361.5  772.47
   385.7  774.29   398.3  776.19   402.6  778.03   415.2  787.41   436.2  789.42
   448.8  801.48   469.8  817.55   478.3   822.3   490.9  827.22   498.2  831.06
#Mann= 8 ,-1,0
       0      .1       0   155.2    .045       0   179.6      .1       0
     190     .05       0     250     .06       0     290     .05       0
     400     .06       0  498.16      .1       0
Bank Sta=155.2,179.6
XS Rating Curve= 0 ,0
Exp/Cntr(USF)=0,0
Exp/Cntr=0.3,0.1

Type RM Length L Ch R = 1 ,3431    ,72.8,72.9,72.9
XS GIS Cut Line= 3
1648970.77458292378503.169535168 1648811.9381044378607.409617744
1648694.67172006378977.068776678
#Sta/Elev= 30
       0  840.71    36.7  838.55      51  835.09    75.4  820.53    89.3  807.34
   109.8  791.43   122.8  784.72   127.1  783.19   151.5  781.42   162.9  776.28
   176.2  768.68   262.5  766.22   266.7  764.85   270.9  762.05   277.4759.4856
   283.5  758.86   296.1  759.47   308.7  764.25   321.3  765.87   375.8  768.38
     401  771.53   423.3  773.29   484.9  775.74   493.7  778.08   514.3   786.5
   539.5  787.18   543.7  788.95   552.1  794.12   564.7  799.63   577.8  806.67
#Mann= 8 ,-1,0
       0     .05       0      30      .1       0     150     .08       0
  239.99     .05       0   277.4    .045       0   296.1     .05       0
  349.99     .06       0  549.99      .1       0
Bank Sta=277.4,296.1
XS Rating Curve= 0 ,0
Exp/Cntr(USF)=0,0
Exp/Cntr=0.3,0.1

Type RM Length L Ch R = 1 ,3358    ,361.8,369.3,379.8
XS GIS Cut Line= 3
1648963.81400655378405.7214659231648797.43690362378411.643407206
 1648626.8061004378953.576831414
#Sta/Elev= 30
       0  843.09    27.7  839.89    39.7  835.96      59   824.7    79.8  811.15
    87.8  804.55    95.8  796.26    99.8  793.34   103.8  791.66   115.8  789.97
   119.8  787.66   127.8  780.71   151.8  774.45   260.7  768.61   339.4  768.86
   393.9  766.84   423.4  764.68     443  759.02   448.4  758.51   462.5759.0272
   481.9  764.81   490.5  766.33     549  769.02   595.2  772.98   621.1  776.91
   662.3  785.75   690.3  786.71   707.3  790.52   723.2  796.74   734.6  800.33
#Mann= 9 ,-1,0
       0     .05       0      20      .1       0     120     .08       0
  216.48     .05       0  326.48     .08       0  426.48     .06       0
     443    .045       0   462.5     .06       0  734.64      .1       0
Bank Sta=443,462.5
XS Rating Curve= 0 ,0
Exp/Cntr(USF)=0,0
Exp/Cntr=0.3,0.1

Type RM Length L Ch R = 1 ,2989    ,481.3,488.8,494.8
XS GIS Cut Line= 2
1649090.87238142378175.1564722261648161.92028752378569.016246514
#Sta/Elev= 30
       0  886.85    11.7   879.1    20.4   880.2    50.8  866.67    89.9  855.41
   124.6  836.81   181.1   824.4   194.2  817.02   208.5  806.06   250.6  786.34
   320.2  769.15   385.3  764.56   402.7   760.5   428.8  766.33   524.4  765.53
   672.1  762.26   686.6  756.68   700.4  756.23   709.1756.6777   732.9  762.94
   776.3  764.07   798.1  777.45   819.8  779.23   837.2  792.94   850.2  807.78
   867.6  815.94   893.7  835.18   927.6  854.64   945.9  863.65    1009   884.9
#Mann= 6 ,-1,0
       0      .1       0     370     .05       0   686.6    .045       0
   709.1     .05       0     800     .06       0     910      .1       0
#XS Ineff= 2 , 0
          427.99   782.7
Permanent Ineff=
       F       F
Bank Sta=686.6,709.1
XS Rating Curve= 0 ,0
Exp/Cntr(USF)=0,0
Exp/Cntr=0.3,0.1

Type RM Length L Ch R = 1 ,2500    ,92.7,92.7,92.7
XS GIS Cut Line= 6
1649032.04370624377888.7536721121648680.11938684378000.684439044
1648574.97535576378011.1852206741648405.29065576377968.382484749
1648332.56868833377950.0380332621648207.57783573378004.314594313
#Sta/Elev= 30
       0  863.69    25.1  851.97    63.5  836.56   100.7  817.92   113.3  809.69
   121.7  806.79   146.8  789.78   159.4  787.08   167.8  781.83     172  780.69
     315  767.45   568.7   758.1   592.2  752.36   601.7  751.78   609.9  752.34
   630.5  761.88   655.3  767.65   671.8  769.18   680.1  773.35   696.6   778.5
   704.8  783.34   734.2  783.86   738.5   785.9   742.4  792.12   747.3  803.45
   751.6   810.6   795.2  838.78   812.3  851.88   838.8  867.12   861.2  882.82
#Mann= 8 ,-1,0
       0      .1       0     200     .05       0     260      .1       0
     300     .05       0   592.2    .045       0   609.9     .05       0
  699.96     .06       0  804.96      .1       0
Bank Sta=592.2,609.9
XS Rating Curve= 0 ,0
Exp/Cntr(USF)=0,0
Exp/Cntr=0.3,0.1

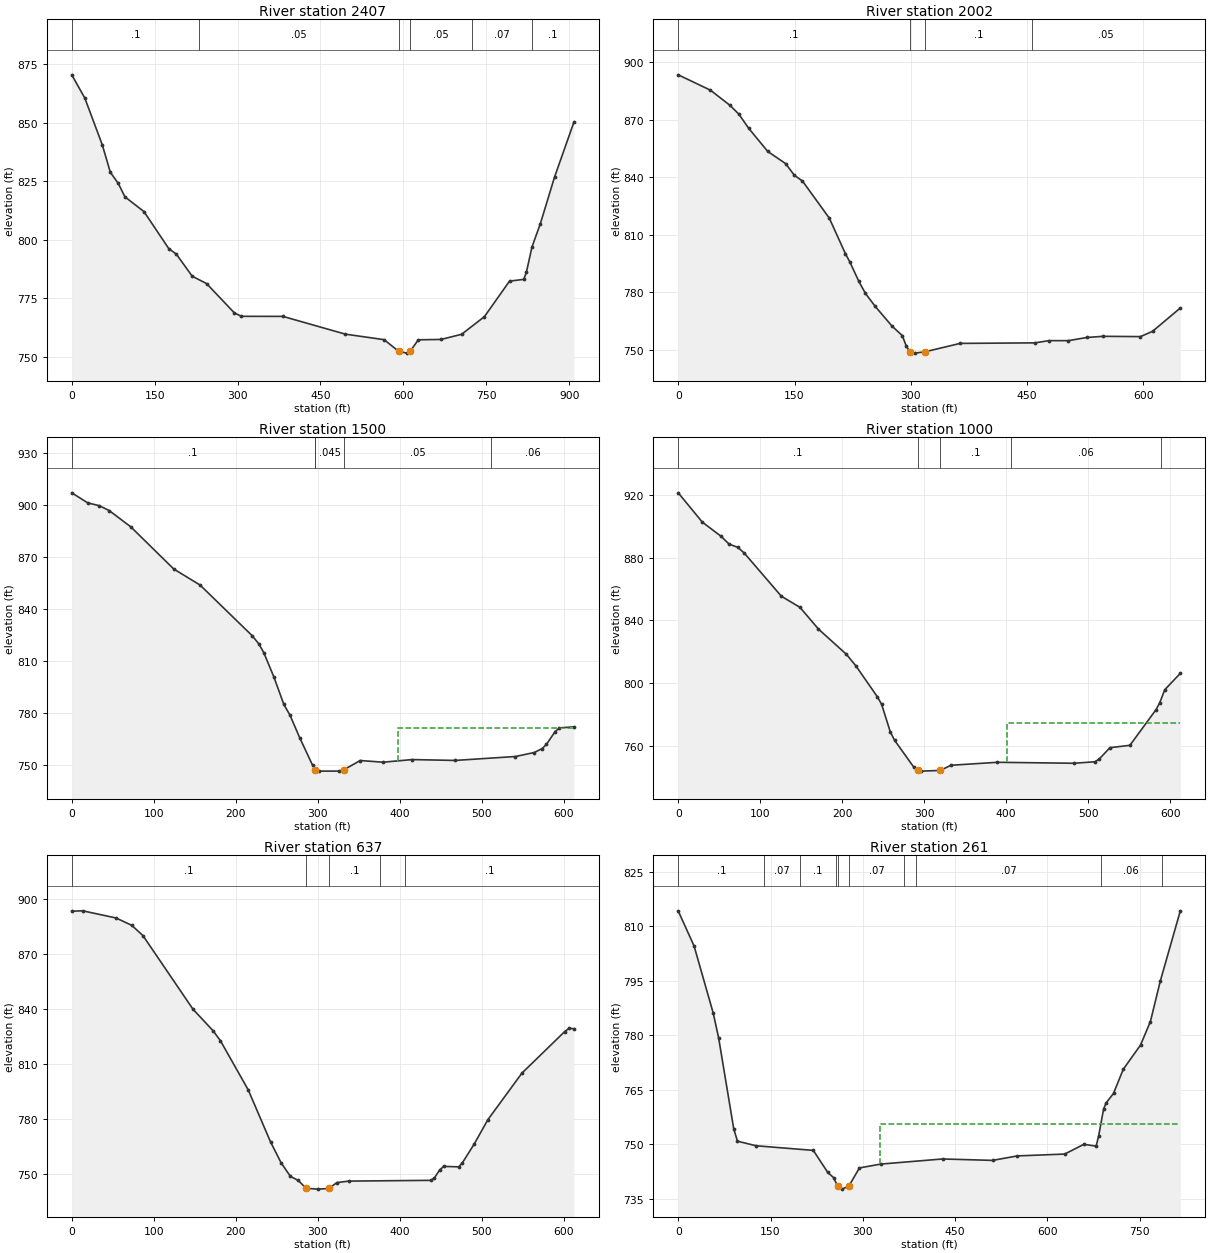
Type RM Length L Ch R = 1 ,2407    ,412,405.2,394.1
XS GIS Cut Line= 6
1649056.68217064377799.3820032621648704.75785125377911.312770195
1648599.61382016377921.8135518241648357.20715274377860.666364412
1648272.36480275377839.2651604821648195.17557897377896.397243997
#Sta/Elev= 30
       0  870.45    23.7  860.46    55.2  840.53    69.8   828.8    84.2  824.02
    96.2  818.31   130.7  811.99   175.4  796.23   189.5  793.74   217.9   784.4
     244  781.23   294.4  768.66     307  767.25     382  767.22   495.1  759.63
   565.2  757.27   591.7752.2546   606.5  751.52   612.2752.2571   627.1  757.22
   668.3  757.37   705.5  759.58   746.7  767.12   792.1  782.28   817.8  783.04
   822.7  786.13   832.7  796.86   847.9  806.83   873.6  826.79   908.5  850.14
#Mann= 6 ,-1,0
       0      .1       0     230     .05       0   591.7    .045       0
   612.2     .05       0  724.96     .07       0  832.46      .1       0
Bank Sta=591.7,612.2
XS Rating Curve= 0 ,0
Exp/Cntr(USF)=0,0
Exp/Cntr=0.3,0.1

Type RM Length L Ch R = 1 ,2002    ,501.5,502.1,500
XS GIS Cut Line= 6
1648749.78898251377312.9300554991648542.36977792377463.302458167
1648458.35157326377526.0064010021648384.43800718377568.586696416
1648297.08253884377611.9744049161648202.96855384377655.543543503
#Sta/Elev= 30
       0  893.39    41.6  885.37    66.8  877.47    78.2   872.9      91  865.46
   115.5  853.45   138.4  847.15   149.9  840.99   160.2  838.07   194.8  818.74
   215.7  800.11   221.5  795.74   232.9  785.79   241.5  779.44     254  772.74
   275.8   762.4     289  757.47   293.9  752.28   298.5 749.046   305.1  748.34
   318.4  749.04   363.6  753.41   460.1  753.69     478  754.85   503.2  754.84
   527.1   756.5     548   757.1   596.2  756.95   611.9  759.73   647.6  771.87
#Mann= 4 ,-1,0
       0      .1       0   298.5    .045       0   318.4      .1       0
  456.33     .05       0
Bank Sta=298.5,318.4
XS Rating Curve= 0 ,0
Exp/Cntr(USF)=0,0
Exp/Cntr=0.3,0.1

Type RM Length L Ch R = 1 ,1500    ,502,500,498.4
XS GIS Cut Line= 6
1648382.62501867376947.5823610131648311.63303468377008.812881589
1648245.37332468377065.961061254  1648188.579475377114.945543334
1647989.80165733377286.3910665961647918.80737676 377347.61929059
#Sta/Elev= 30
       0  906.91    19.5  901.12    33.7  899.48    45.6  896.71      72  887.32
   124.4  863.06   156.5  853.82   219.9  824.73   228.1  820.03   234.2  814.94
   246.4  801.07   258.7  785.11   266.2  778.89     278  765.96   293.8  750.02
   297.2 747.539   301.6  746.66   325.8  746.69   332.2  747.52   351.9  752.77
   379.7   751.8   415.3  753.31   467.6  752.82   541.3  755.08     564  757.36
   573.8  759.61   579.1   762.1   589.5  769.31   594.9  771.53   612.5  772.16
#Mann= 5 ,-1,0
       0      .1       0  296.25     .05       0   297.2    .045       0
   332.2     .05       0  511.25     .06       0
#XS Ineff= 2 , 0
                          398.57          771.76
Permanent Ineff=
       F       F
Bank Sta=297.2,332.2
XS Rating Curve= 0 ,0
Exp/Cntr(USF)=0,0
Exp/Cntr=0.3,0.1

Type RM Length L Ch R = 1 ,1000    ,360.8,362.6,364.6
XS GIS Cut Line= 6
1648030.91410792376541.8466239271647969.17932326376612.400616676
1647911.56034401376678.2512067561647862.17264751376734.694335341
1647689.31570975376932.2464336751647627.58059701377002.800426424
#Sta/Elev= 30
       0  921.21    29.4  902.53    52.1   893.6      62  888.56    72.7  886.46
    80.4  882.93   125.8  855.35   148.5  848.27   171.1  834.41   205.2  818.32
   216.9  810.87   242.8  791.37   248.1  786.53   258.7  768.94     264  763.53
   287.4  746.44     292 744.395   295.8  743.94   319.5744.3612   332.7  747.67
   389.4  749.57     483  748.95   508.5  749.91   513.8  751.77   526.6  758.87
     551  760.38   582.9  783.11   587.4   787.5   593.5  795.77   612.5  806.23
#Mann= 5 ,-1,0
       0      .1       0     292    .045       0   319.5      .1       0
  406.25     .06       0  588.75      .1       0
#XS Ineff= 2 , 0
                          400.88          774.45
Permanent Ineff=
       F       F
Bank Sta=292,319.5
XS Rating Curve= 0 ,0
Exp/Cntr(USF)=0,0
Exp/Cntr=0.3,0.1

Type RM Length L Ch R = 1 ,637     ,373.8,375.8,377.3
XS GIS Cut Line= 6
1647779.51751082376343.7766722151647708.60885999376405.103977383
1647510.06398149376576.8195132181647453.33738891376625.881422968
1647387.15510658376683.119169385   1647316.24744376744.447458805
#Sta/Elev= 30
       0  893.13    13.4  893.32      54  889.43    73.2   885.4    86.8  879.84
   147.9  839.67   172.4  827.94   181.3  822.54   215.2  795.76   242.5  767.34
   255.3     756   266.7  748.56   276.3  746.33   285.9742.0135   300.7  741.59
   313.6741.9542   323.4  745.14   337.7  745.97   438.2  746.38   442.5  747.75
   448.7     752   453.7  753.99     472  753.74   476.5  755.92   490.7  765.99
   507.7  779.51   549.2  804.85   601.3  827.47   606.5  829.22   612.5  829.07
#Mann= 5 ,-1,0
       0      .1       0   285.9    .045       0   313.6      .1       0
  376.25     .06       0  406.25      .1       0
Bank Sta=285.9,313.6
XS Rating Curve= 0 ,0
Exp/Cntr(USF)=0,0
Exp/Cntr=0.3,0.1

Type RM Length L Ch R = 1 ,261     ,90.2,88.6,89
XS GIS Cut Line= 4
1647521.23264583376315.8603714451647453.56037552376174.070852701
1647248.93232006376298.1366816021647274.71223256376717.060259708
#Sta/Elev= 30
       0  814.23    25.8  804.57    56.9  786.11    65.7  779.27    90.3   754.2
    96.3  750.88   126.3  749.62   219.6  748.34     243  742.29   252.4  740.86
     259  738.58   266.4  737.68   277.6  738.58   294.5  743.51   328.9  744.57
   429.7  745.98   510.9  745.59   551.1  746.82   628.2  747.33   659.3  750.01
   679.3  749.51   683.4  752.36   691.4  759.73   695.4  761.37   707.5  764.02
   723.4  770.67   751.5  777.35   767.5  783.81   783.5   794.9   816.1  814.27
#Mann= 10 ,-1,0
       0      .1       0     140     .07       0  197.11      .1       0
  257.11     .07       0     259    .045       0   277.6     .07       0
  367.11     .06       0  387.11     .07       0  686.41     .06       0
  786.41      .1       0
#XS Ineff= 2 , 0
                          328.19          755.66
Permanent Ineff=
       F       F
Bank Sta=259,277.6
XS Rating Curve= 0 ,0
Exp/Cntr(USF)=0,0
Exp/Cntr=0.3,0.1

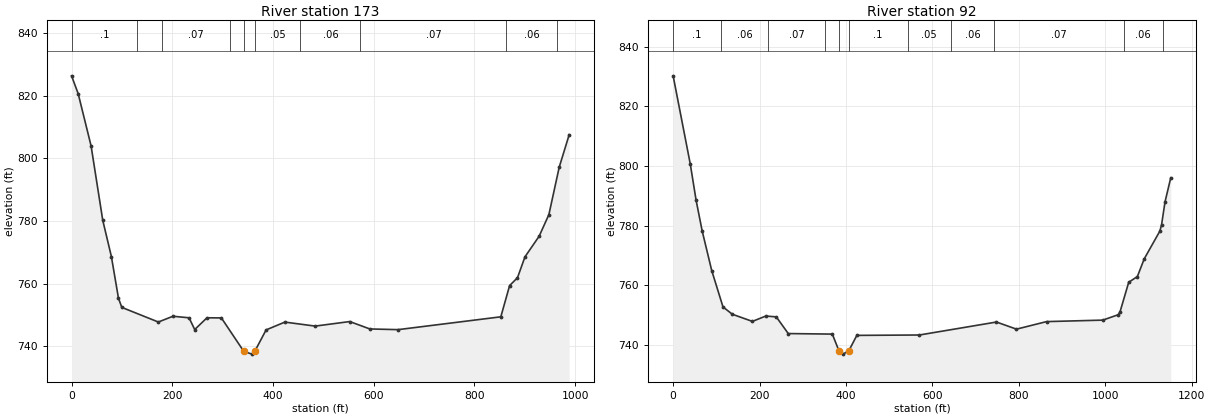
Type RM Length L Ch R = 1 ,173     ,76.1,80.8,84.6
XS GIS Cut Line= 4
1647562.31938138376295.7198148051647433.41981888376087.869270283
1647228.79176342376211.9350991841647241.68171967376716.254637443
#Sta/Elev= 30
       0  826.31    13.2   820.6    38.8  803.97      62  780.21    79.1  768.68
    93.2  755.37    99.8  752.45   172.4  747.78   201.4  749.62   233.4  749.13
   244.6  745.38     269  749.13   297.6  749.09   342.1  738.42   358.4  737.54
   363.9738.4248   386.4  745.26   423.7  747.76   483.9  746.48   552.5  747.93
   592.5  745.57   648.5  745.35   852.6  749.44   870.1  759.41   885.7   761.9
   900.6  768.58   928.7  775.14   948.1  782.05   968.6  797.16   988.4  807.54
#Mann= 10 ,-1,0
       0      .1       0     130     .06       0     180     .07       0
  314.58     .05       0   342.1    .045       0   363.9     .05       0
  454.58     .06       0  573.88     .07       0  863.88     .06       0
  963.88      .1       0
Bank Sta=342.1,363.9
XS Rating Curve= 0 ,0
Exp/Cntr(USF)=0,0
Exp/Cntr=0.3,0.1

Type RM Length L Ch R = 1 ,92      ,,,
XS GIS Cut Line= 4
 1647622.7410513376269.1342800411647414.89050678376051.616268332
1647186.09378335376087.0636480171647208.65120678 376705.78154799
#Sta/Elev= 30
       0  830.27    39.6  800.74    53.2  788.49    67.2  778.23    89.3  764.93
   115.4  752.72     137  750.27   183.4  747.87   214.5  749.67   238.7  749.39
   266.4  743.79   368.4  743.61   383.8 737.954   392.7  736.89   406.2737.9247
   425.1  743.18   569.9  743.31   748.2  747.66   794.5  745.27     864   747.8
   994.2   748.3  1030.1  750.12  1034.2  751.12  1054.2  761.01  1074.2  762.91
  1090.2  768.89  1126.3  778.18  1130.3  780.37  1138.2  787.97  1151.5  796.07
#Mann= 11 ,-1,0
       0      .1       0     110     .06       0     220     .07       0
  350.86      .1       0   383.8    .045       0   406.2      .1       0
  542.39     .05       0  642.39     .06       0  742.39     .07       0
 1042.39     .06       0 1132.39      .1       0
Bank Sta=383.8,406.2
XS Rating Curve= 0 ,0
Exp/Cntr(USF)=0,0
Exp/Cntr=0.3,0.1
LCMann Table=0

Chan Stop Cuts=-1
Use User Specified Reach Order=0
Composite Channel Slope=5